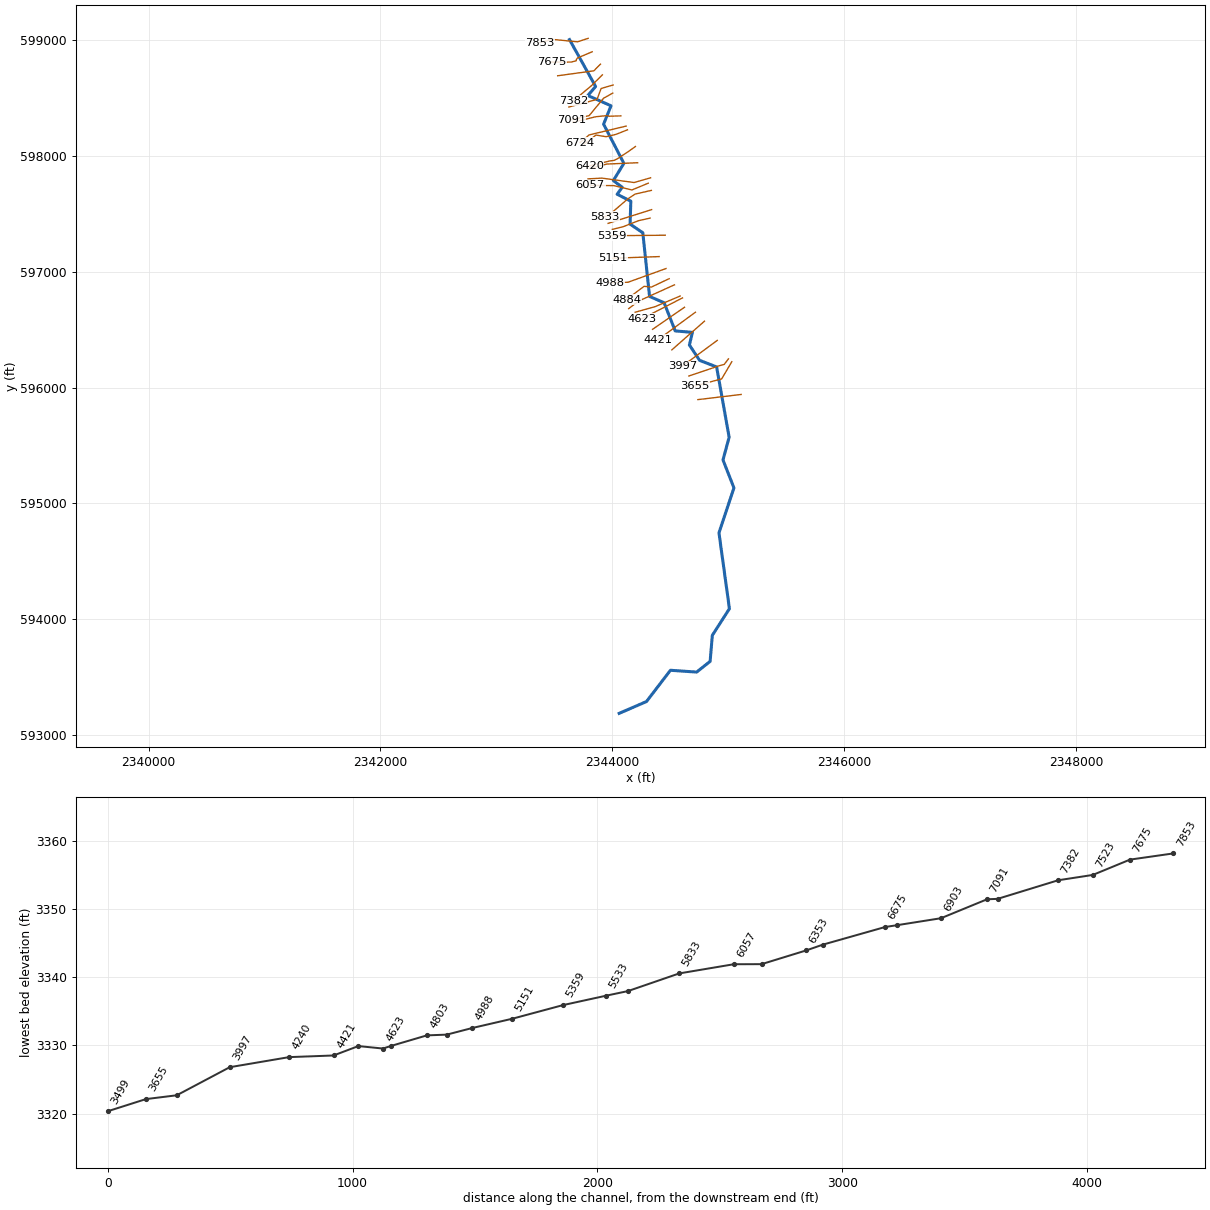
--- MLNXRN.prj (project) ---

Proj Title=MLNXRN
Current Plan=p01
Default Exp/Contr=0,0
English Units
Geom File=g01
Flow File=f01
Plan File=p01
Background Map Layer=Inundation Boundary (01pct Value_0)
BEGIN DESCRIPTION:
----------MODEL BY WOOD PLC 2021----------
Stream Name: Mullenax Run
Flood Zone: Enhanced Approximate
Pocahontas County, WV
HEC-RAS Version: RAS 6.0
Vertical Datum: NAVD88
Projection: NAD 1983 StatePlane West Virginia S FIPS 4702 (US Feet)
Terrain: 1-meter LIDAR (FEMA Region III 3DEP collected 2016-2018)
Land Use: 2016 NLCD
Hydrologic Method:
WV SIR2010-5033 regression equations weighted with gage ######
Model Notes:
END DESCRIPTION:
DSS Export Rating Curves= 0
DSS Export Rating Curve Sorted= 0
DSS Export Volume Flow Curves= 0
DXF OffsetX= 0
DXF OffsetY= 0
DXF ScaleX= 0
DXF ScaleY= 0

--- MLNXRN.p01 (plan) ---

Plan Title=Floodplain
Program Version=6.00
Short Identifier=Floodplain
Geom File=g01
Flow File=f01
Subcritical Flow
K Sum by GR= 0
Std Step Tol= 0.01
Critical Tol= 0.01
Num of Std Step Trials= 20
Max Error Tol= 0.3
Flow Tol Ratio= 0.001
Split Flow NTrial= 30
Split Flow Tol= 0.02
Split Flow Ratio= 0.02
Log Output Level= 0
Friction Slope Method= 1
Unsteady Friction Slope Method= 2
Unsteady Bridges Friction Slope Method= 1
Parabolic Critical Depth
Global Vel Dist= 0 , 0 , 0
Global Log Level= 0
CheckData=True
Encroach Param=-1 ,0,0, 0
Mapping Interval=1HOUR
Computation Time Step Use Courant=        0
Computation Time Step Use Time Series=    0
Computation Time Step Count To Double=0
Computation Time Step Max Doubling=0
Computation Time Step Max Halving=0
Computation Time Step Residence Courant=0
Run HTab= 0
Run UNet= 0
Run Sediment= 0
Run PostProcess= 0
Run WQNet= 0
Run RASMapper=-1
UNET Theta= 0
UNET Theta Warmup= 0
UNET ZTol= 0
UNET ZSATol= 0
UNET MxIter= 0
UNET Max Iter WO Improvement= 0
UNET MaxInSteps= 0
UNET DtIC= 0
UNET DtMin= 0
UNET MaxCRTS= 0
UNET WFStab= 0
UNET SFStab= 0
UNET WFX= 1
UNET SFX= 1
UNET Gravity=32.174
UNET 1D Methodology=Finite Difference
UNET DSS MLevel= 1
UNET Pardiso=0
UNET DZMax Abort= 0
UNET Use Existing IB Tables= 0
UNET Froude Reduction=False
UNET Froude Limit= 0
UNET Froude Power= 0
UNET D1 Cores= 0
UNET WindReference=Eulerian
UNET WindDragFormulation=Hsu (1988)
UNET D2 Coriolis=0
UNET D2 Cores= 0
UNET D2 Theta= 1
UNET D2 Theta Warmup= 1
UNET D2 Z Tol= 0.01
UNET D2 Volume Tol= 0.01
UNET D2 Max Iterations= 20
UNET D2 Equation= 0
UNET D2 RampUpFraction=0.1
UNET D2 TimeSlices= 1
UNET D2 Turbulence Formulation=Non-Conservative (original)
UNET D2 Eddy Viscosity=0.3
UNET D2 Transverse Eddy Viscosity=0.1
UNET D2 Smagorinsky Mixing=0
UNET D2 BCVolumeCheck=0
UNET D2 Cores=0
UNET D2 SolverType=PARDISO (Direct)
UNET D2 Minimum Iterations= 2147483647
UNET D2 Maximum Iterations= 2147483647
UNET D2 Restart Number= 10
UNET D2 Relaxation Coeff=1.3
UNET D2 SOR Precondition Iterations= 10
UNET D2 ILUT Maximum Fill= 8
UNET D2 ILUT Tolerance=1E-08
UNET D1D2 MaxIter= 0
UNET D1D2 ZTol=0.01
UNET D1D2 QTol=0.1
UNET D1D2 MinQTol=1
Write IC File= 0
Write IC File at Fixed DateTime=0
Write IC File at Sim End=0
Echo Input=False
Echo Parameters=False
Echo Output=False
Write Detailed= 0
HDF Write Warmup=0
HDF Write Time Slices=0
HDF Flush=0
HDF Compression= 1
HDF Chunk Size= 1
HDF Spatial Parts= 1
HDF Use Max Rows=0
HDF Fixed Rows= 1
Calibration Method= 0
Calibration Iterations= 20
Calibration Max Change=0.05
Calibration Tolerance=0.2
Calibration Maximum=1.5
Calibration Minimum=0.5
Calibration Optimization Method= 1
WQ AD Non Conservative
WQ ULTIMATE=-1
WQ Max Comp Step=1HOUR
WQ Output Interval=15MIN
WQ Output Selected Increments= 0
WQ Output face flow=0
WQ Output face velocity=0
WQ Output face area=0
WQ Output face dispersion=0
WQ Output cell volume=0
WQ Output cell surface area=0
WQ Output cell continuity=0
WQ Output cumulative cell continuity=0
WQ Output face conc=0
WQ Output face dconc_dx=0
WQ Output face courant=0
WQ Output face peclet=0
WQ Output face adv mass=0
WQ Output face disp mass=0
WQ Output cell mass=0
WQ Output cell source sink temp=0
WQ Output nsm pathways=0
WQ Output nsm derived pathways=0
WQ Create Restart=0
WQ Fixed Restart=0
WQ System Summary=0
WQ Write To DSS=0
Sorting and Armoring Iterations= 10
XS Update Threshold= 0.02
Bed Roughness Predictor= 0
Hydraulics Update Threshold= 0.02
Energy Slope Method= 1
Volume Change Method= 1
Sediment Retention Method= 0
Sediment TS Multiplier= 1
Warm Up Method= 0
XS Weighting Method= 0
Number of US Weighted Cross Sections= 1
Number of DS Weighted Cross Sections= 1
Upstream XS Weight=0
Main XS Weight=1
Downstream XS Weight=0
Number of DS XS's Weighted with US Boundary= 1
Upstream Boundary Weight= 1
Weight of XSs Associated with US Boundary= 0
Number of US XS's Weighted with DS Boundary= 1
Downstream Boundary Weight= 0.5
Weight of XSs Associated with DS Boundary= 0.5
Percentile Method= 0
Sediment Output Level= 3
Mass or Volume Output= 0
Output Increment Type= 1
Profile and TS Output Increment= 1
Transport Output Increment 1
XS Output Flag= 0
XS Output Increment= 10
Read HDF5 Sediment Hotstart= 0
Sediment Hotstart Type= 0
Write Gradation File= 0
Read Gradation Hotstart= 0
Write HDF5 File= 1
Write Binary Output= 1
Write DSS Sediment File= 0
DSS Sediment Output Type= 1
SV Curve= 0
Specific Gage Flag= 0
Subcell Erosion Methods= 0
Subcell Deposition Methods= 0
Advection Scheme= 1
Matrix Solver= 0
Implicit Weighting Factor= 1
Maximum Outer Loop Convergence Iterations= 5
Convergence Maximum Absolute= 0.001
Convergence RMSE= 0.0001
Grain Fractions Max Abs Error= 0.001
Max Subgrid Regions= 1
Max Subgrid Length Scale= 3.402823E+38
Initial Layer Thickness= 3.402823E+38
Min Layer Thickness= 3.402823E+38
Max Layer Thickness= 3.402823E+38
Number of Layers= 5

--- MLNXRN.f01 (steady flow) ---

Flow Title=Flow
Program Version=6.00
Number of Profiles= 6
Profile Names=01pct,10pct,04pct,02pct,0_2pct,01plus
River Rch & RM=MLNXRN,Main,7853
     705     376     497     598     981    1040
River Rch & RM=MLNXRN,Main,3655
     803     430     568     682    1120    1190
Boundary for River Rch & Prof#=MLNXRN,Main            , 1
Up Type= 0
Dn Type= 3
Dn Slope=0.02961
Boundary for River Rch & Prof#=MLNXRN,Main            , 2
Up Type= 0
Dn Type= 3
Dn Slope=0.02961
Boundary for River Rch & Prof#=MLNXRN,Main            , 3
Up Type= 0
Dn Type= 3
Dn Slope=0.02961
Boundary for River Rch & Prof#=MLNXRN,Main            , 4
Up Type= 0
Dn Type= 3
Dn Slope=0.02961
Boundary for River Rch & Prof#=MLNXRN,Main            , 5
Up Type= 0
Dn Type= 3
Dn Slope=0.02961
Boundary for River Rch & Prof#=MLNXRN,Main            , 6
Up Type= 0
Dn Type= 3
Dn Slope=0.02961
DSS Import GetInterval= 0
DSS Import GetPeak= 0
DSS Import FillOption= 0

--- MLNXRN.g01 (geometry) ---

Geom Title=Geometry
Program Version=6.00

River Reach=MLNXRN          ,Main
Reach XY= 30
     2343631.939      599001.757     2343857.032      598597.116
2343789.93842759598519.4063162932343989.89775865598430.630857439
2343925.91467574598272.2903039532344100.67658427597934.271363719
2344009.77153152597785.5176410422344086.97660873597727.759585328
2344042.47867254597667.8309131992344160.72117234 597607.90224107
     2344154.409      597410.1942344264.09346665597335.246699296
     2344322.417      596785.9382344447.97548218596731.802901855
2344543.56822932596488.730613008     2344692.241      596476.185
2344666.05661301596366.9719415682344753.93683242596234.923331865
2344900.97727784596177.8608302122345008.80385733595571.886449223
2344955.94660703595375.2904403032345050.24205801595134.548620996
2344921.10084736594746.7718225622345011.39374487594092.472051556
 2344863.8878771593862.6783932252344844.81688701593637.946787818
2344728.50739191 593545.652613572344502.48520082593561.148505491
2344295.70872798593291.420874091     2344059.991      593189.422

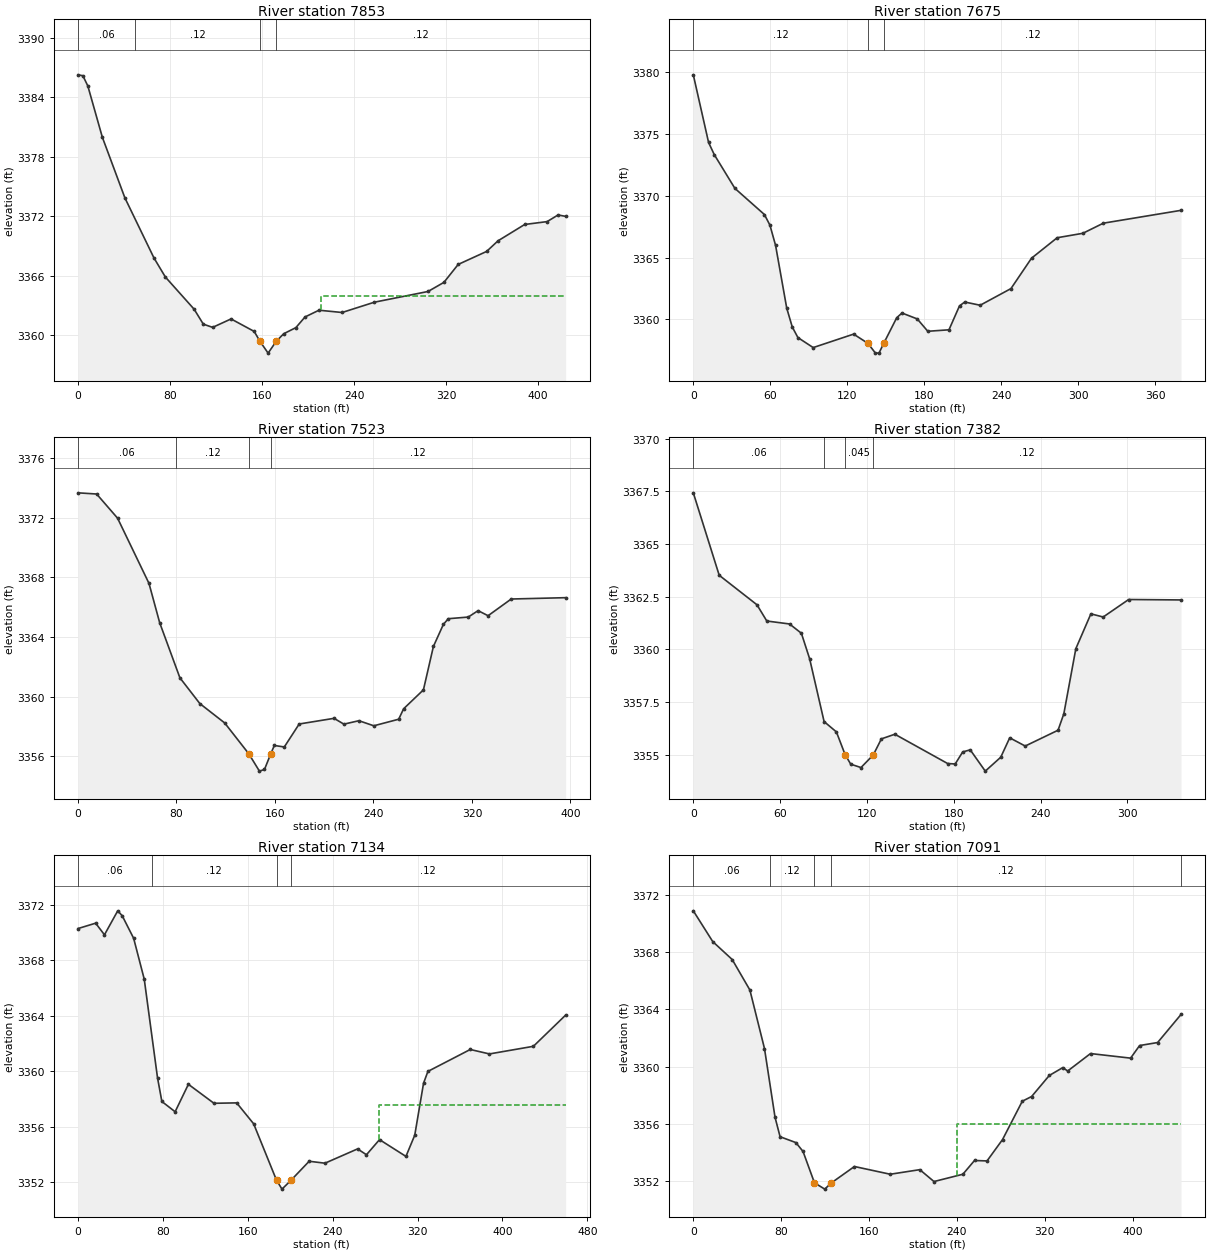
Type RM Length L Ch R = 1 ,7853    ,156.3,177.5,156.3
XS GIS Cut Line= 4
2343792.29054736599012.670436536 2343701.9075302598982.680486441
2343485.27061953599003.6453487642343377.75428945598976.044860316
#Sta/Elev= 30
       0 3386.25     4.3 3386.16     8.6 3385.13    21.2 3379.96    40.8 3373.84
    66.1 3367.77      76 3365.85     101  3362.6     109 3361.09   117.1 3360.77
   133.1 3361.62   153.2 3360.36   158.33359.344   165.3 3358.17   172.4 3359.37
   178.9 3360.13   189.4 3360.74   197.4 3361.82   209.5  3362.5   229.6 3362.27
   257.7 3363.31   304.3 3364.39   318.1 3365.31   330.5 3367.12   355.2 3368.43
   365.1  3369.5   388.3 3371.15   407.8 3371.44   417.3 3372.11   423.9 3371.97
#Mann= 4 ,-1,0
       0     .06       0      50     .12       0   158.3    .045       0
   172.4     .12       0
#XS Ineff= 2 , 0
                          210.89         3363.93
Permanent Ineff=
       F       F
Bank Sta=158.3,172.4
XS Rating Curve= 0 ,0
Exp/Cntr=0.3,0.1

Type RM Length L Ch R = 1 ,7675    ,158.5,152,141.7
XS GIS Cut Line= 6
2343827.14665082598896.7602926162343700.85466324598843.058239974
  2343691.580917598831.5764589162343688.93127522598818.328250003
2343644.49483945598807.8955504472343475.67909192598807.353644691
#Sta/Elev= 30
       0 3379.81    11.9 3374.33    16.3 3373.35    32.4 3370.61    55.4 3368.49
    59.7 3367.63    64.1 3365.99    72.8  3360.9    77.1 3359.38    81.5 3358.52
    93.4 3357.71   124.9  3358.8   136.1 3358.05   141.9 3357.26   144.7 3357.27
   148.4 3358.06   158.5 3360.13   162.6 3360.51   174.5 3360.03   182.7 3359.03
   199.2 3359.15   207.4 3361.09   211.5  3361.4   223.5 3361.14   247.5 3362.49
   263.5 3364.95   283.5 3366.61   303.5 3366.97   319.5 3367.79     380 3368.83
#Mann= 3 ,-1,0
       0     .12       0   136.1    .045       0   148.4     .12       0
Bank Sta=136.1,148.4
XS Rating Curve= 0 ,0
Exp/Cntr(USF)=0,0
Exp/Cntr=0.3,0.1

Type RM Length L Ch R = 1 ,7523    ,129.9,141.4,148.9
XS GIS Cut Line= 3
2343898.85017626598790.1849323872343841.67327902598732.372736285
2343529.74153961598689.807712782
#Sta/Elev= 30
       0 3373.67    15.2 3373.59    32.2 3371.97    57.7  3367.6    66.4 3364.96
    82.8 3361.27      99 3359.54   119.2 3358.24   138.8 3356.17   147.4 3355.01
   151.5 3355.12   156.5 3356.15   159.5 3356.73   167.6 3356.63   179.7 3358.17
     208 3358.55     216 3358.16   228.2 3358.39   240.3 3358.05   260.5 3358.49
   264.5 3359.19   280.6 3360.46   288.7 3363.37   296.8 3364.85   300.8 3365.23
     317 3365.34     325 3365.77   333.1 3365.43   351.9 3366.55   396.1 3366.64
#Mann= 4 ,-1,0
       0     .06       0      80     .12       0   138.8    .045       0
   156.5     .12       0
Bank Sta=138.8,156.5
XS Rating Curve= 0 ,0
Exp/Cntr(USF)=0,0
Exp/Cntr=0.3,0.1

Type RM Length L Ch R = 1 ,7382    ,242.8,247.5,247.7
XS GIS Cut Line= 3
2343915.41189088 598697.799485882343821.18086676598604.304641631
2343664.37455317598473.264623705
#Sta/Elev= 30
       0 3367.43    17.9 3363.52      44 3362.12    50.8 3361.35    66.5 3361.21
    74.7 3360.77    80.4 3359.56    90.4 3356.58    98.9 3356.09   104.93355.017
   108.8 3354.56   115.9  3354.4   124.4    3355     130 3355.76   139.3 3355.98
   175.8 3354.59     181 3354.57   186.2 3355.14   191.4 3355.24   201.8 3354.23
   212.5 3354.89   218.7 3355.81   229.4 3355.42   252.1 3356.17   256.1 3356.95
   264.4 3360.04   274.8 3361.69   283.3 3361.54   300.9 3362.37   337.1 3362.35
#Mann= 4 ,-1,0
       0     .06       0      90     .12       0   104.9    .045       0
   124.4     .12       0
Bank Sta=104.9,124.4
XS Rating Curve= 0 ,0
Exp/Cntr(USF)=0,0
Exp/Cntr=0.3,0.1

Type RM Length L Ch R = 1 ,7134    ,46.5,43,38.5
XS GIS Cut Line= 4
2344008.17055526598610.1940806382343904.36919274598580.010705723
 2343869.0325587598485.779681597 2343626.8293795598420.259672634
#Sta/Elev= 30
       0 3370.29    16.7 3370.68      25 3369.84    37.5 3371.57    41.7 3371.22
    52.5 3369.59    62.5 3366.64      75 3359.53    79.1 3357.82    91.6 3357.08
   104.1 3359.06   128.2 3357.69   149.6 3357.72   165.6 3356.21  187.15 3352.14
   192.3  3351.5   200.8 3352.14   217.9 3353.51   232.8 3353.37   263.5  3354.4
   271.9 3353.98   284.2 3355.07   309.1 3353.86   317.4 3355.39   325.7 3359.14
   329.8 3359.99   369.7 3361.57   387.8 3361.25   429.2  3361.8   459.6 3364.05
#Mann= 4 ,-1,0
       0     .06       0      70     .12       0  187.15    .045       0
   200.8     .12       0
#XS Ineff= 2 , 0
                          283.94          3357.6
Permanent Ineff=
       F       F
Bank Sta=187.15,200.8
XS Rating Curve= 0 ,0
Exp/Cntr(USF)=0,0
Exp/Cntr=0.3,0.1

Type RM Length L Ch R = 1 ,7091    ,199.1,188.3,173.1
XS GIS Cut Line= 4
2344005.22583575 598540.256992422343925.71840915598496.086199861
2343801.30401011 598345.905505162343647.44241603598309.832691237
#Sta/Elev= 30
       0 3370.88    17.7 3368.73    35.4 3367.48    51.5 3365.35    64.8 3361.26
    74.4 3356.46      79  3355.1    93.4 3354.69    99.9 3354.07   110.3 3351.88
   119.7 3351.44   125.4 3351.86   146.7 3353.02   179.3 3352.48   206.2  3352.8
   219.1 3351.97   245.4 3352.48     256 3353.44   267.4 3353.41   281.5  3354.9
   299.5 3357.58     308 3357.91   324.1 3359.38   336.4 3359.93   340.8 3359.69
   361.6 3360.91   398.1 3360.59   406.3 3361.47   422.7 3361.68     444 3363.64
#Mann= 5 ,-1,0
       0     .06       0      70     .12       0   110.3    .045       0
   125.4     .12       0  444.01      .1       0
#XS Ineff= 2 , 0
                          239.72         3355.97
Permanent Ineff=
       F       F
Bank Sta=110.3,125.4
XS Rating Curve= 0 ,0
Exp/Cntr(USF)=0,0
Exp/Cntr=0.3,0.1

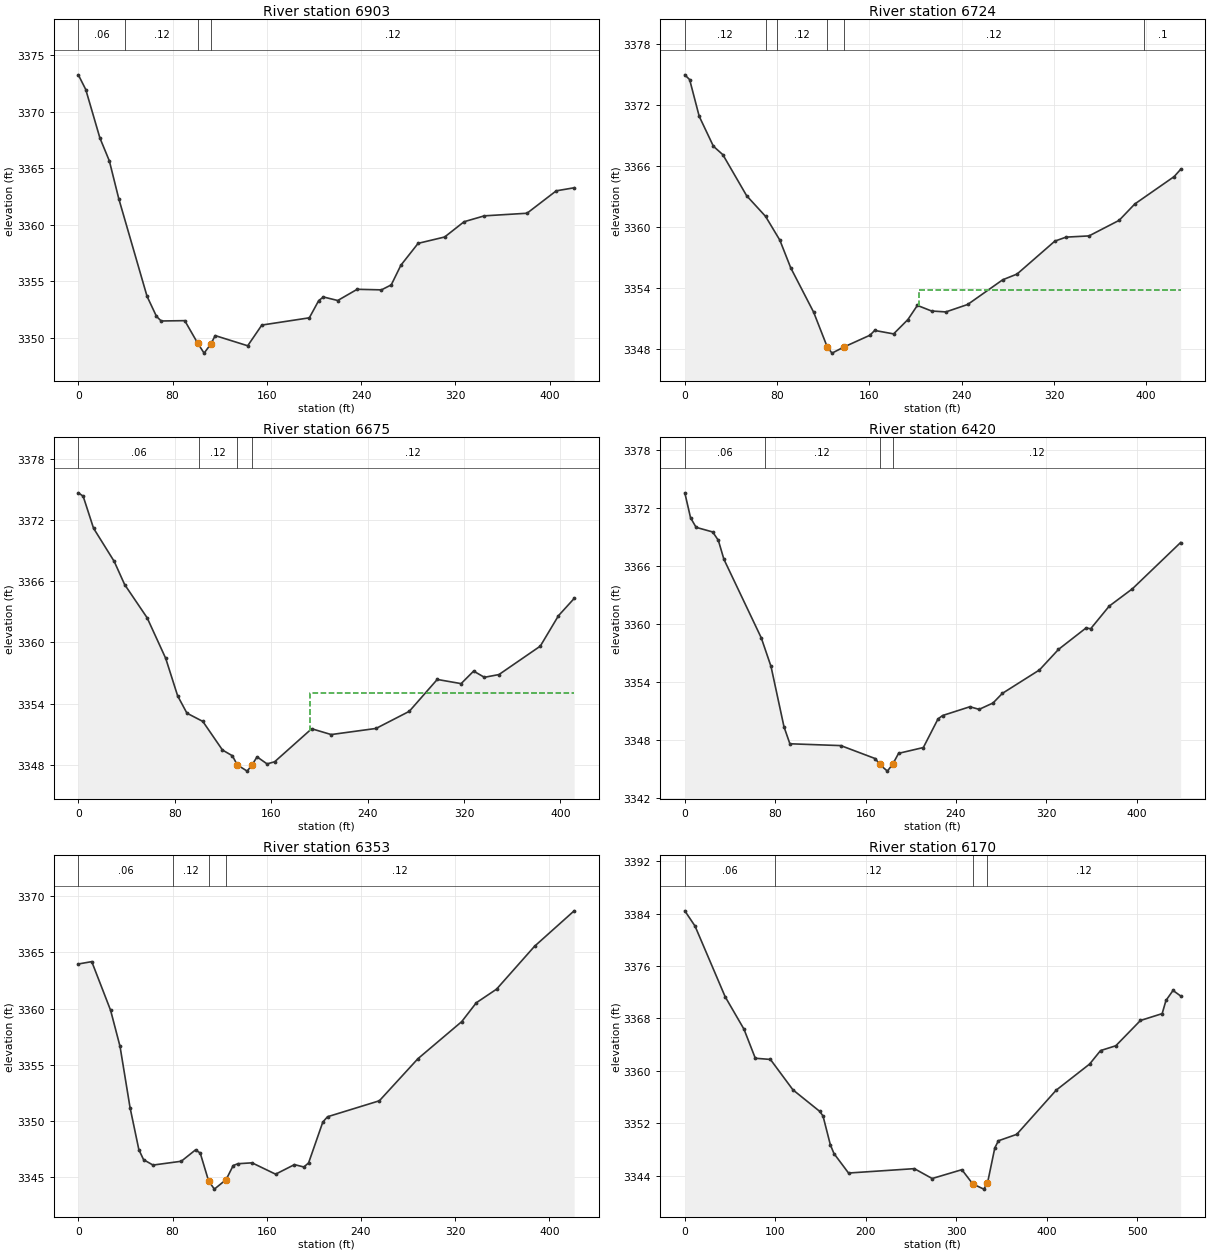
Type RM Length L Ch R = 1 ,6903    ,169,179.1,181.9
XS GIS Cut Line= 5
 2344074.4267441598343.6969655322343972.83392121598340.752246028
2343959.58268344598346.6416850362343858.72604043598336.335166772
2343661.42983367598287.747294957
#Sta/Elev= 30
       0 3373.25     6.3 3371.95    18.3 3367.67    26.3 3365.65    34.3 3362.31
    58.3 3353.68    66.3 3351.91    70.3  3351.5    90.3 3351.53   101.33349.534
   106.7 3348.66   112.5 3349.47   116.1 3350.21   143.7 3349.31   155.7 3351.14
     196 3351.78     204 3353.31     208 3353.62   220.1 3353.31   236.6  3354.3
   257.2 3354.25   265.5 3354.69   273.7 3356.43   288.3 3358.36   310.8 3358.92
   327.3 3360.27   344.5 3360.79   380.7 3361.02   405.5    3363   420.7 3363.27
#Mann= 4 ,-1,0
       0     .06       0      40     .12       0   101.3    .045       0
   112.5     .12       0
Bank Sta=101.3,112.5
XS Rating Curve= 0 ,0
Exp/Cntr(USF)=0,0
Exp/Cntr=0.3,0.1

Type RM Length L Ch R = 1 ,6724    ,49.2,49.1,49.1
XS GIS Cut Line= 3
2344120.29687298598255.5905773762343801.11185313598179.585556423
  2343723.424803598113.960985881
#Sta/Elev= 30
       0 3374.99     4.2 3374.52    12.5 3370.91    24.8 3367.97      33 3367.14
    53.6 3363.11      70 3361.08    82.4 3358.74    91.8 3356.03   111.7 3351.66
   123.5 3348.24   127.6 3347.64   138.3 3348.26   160.5  3349.4   164.6 3349.87
     181 3349.53   193.4 3350.94   201.6 3352.33   213.9 3351.78   226.3 3351.69
   245.2 3352.42   275.6 3354.85     288 3355.41   320.8 3358.65   330.5 3359.04
   350.4 3359.16   376.5 3360.69   390.1  3362.3   424.2 3364.99   429.8  3365.7
#Mann= 6 ,-1,0
       0     .12       0      70     .06       0      80     .12       0
   123.5    .045       0   138.3     .12       0  398.11      .1       0
#XS Ineff= 2 , 0
                           203.1         3353.82
Permanent Ineff=
       F       F
Bank Sta=123.5,138.3
XS Rating Curve= 0 ,0
Exp/Cntr=0.3,0.1

Type RM Length L Ch R = 1 ,6675    ,248.3,254.6,256
XS GIS Cut Line= 5
2344131.84877442598223.6996457472344033.93685092 598184.68211232
2343947.80380543598164.0690757922343860.19840018598178.056493436
2343757.86939742598100.021426582
#Sta/Elev= 30
       0 3374.69       4 3374.36    12.6 3371.22    29.8 3367.95    38.4 3365.69
    57.1 3362.42    72.5 3358.44    82.4 3354.76    90.1 3353.06   103.3 3352.25
   119.6 3349.44   127.8 3348.88   131.9 3347.98   140.1 3347.37   144.2    3348
   148.3 3348.77   156.6 3348.08   162.9 3348.29   193.6 3351.53   209.8 3350.96
     247 3351.56   274.6 3353.24   297.8 3356.37   317.6 3355.96     328 3357.19
   336.9 3356.58     349 3356.85   383.3 3359.64   398.4 3362.63   411.4 3364.32
#Mann= 4 ,-1,0
       0     .06       0     100     .12       0   131.9    .045       0
   144.2     .12       0
#XS Ineff= 2 , 0
                          191.83         3355.06
Permanent Ineff=
       F       F
Bank Sta=131.9,144.2
XS Rating Curve= 0 ,0
Exp/Cntr(USF)=0,0
Exp/Cntr=0.3,0.1

Type RM Length L Ch R = 1 ,6420    ,74.4,67.4,60.4
XS GIS Cut Line= 6
2344200.31350289598079.4083900542344142.52338262598038.182316999
2344045.71572893597974.1346677892344015.90044395597959.411070269
2343983.87661935597955.7301708892343802.77636986597912.295558206
#Sta/Elev= 30
       0 3373.57     5.1 3370.99      10    3370    24.7 3369.52    29.7 3368.65
    34.6  3366.7    67.7 3358.56    76.3 3355.61    87.8 3349.36      93 3347.61
   138.1 3347.42   168.7 3346.07  172.36 3345.48   179.3 3344.78   184.1 3345.52
   189.2 3346.62   211.1 3347.22   224.1 3350.18   228.1 3350.53   252.3 3351.44
   260.5 3351.17   272.8 3351.83     281 3352.82   313.9 3355.25   330.7 3357.37
   355.1 3359.59   359.2 3359.51   375.6 3361.85   396.2 3363.65   438.8 3368.43
#Mann= 4 ,-1,0
       0     .06       0   70.99     .12       0  172.36    .045       0
   184.1     .12       0
Bank Sta=172.36,184.1
XS Rating Curve= 0 ,0
Exp/Cntr(USF)=0,0
Exp/Cntr=0.3,0.1

Type RM Length L Ch R = 1 ,6353    ,181.4,182.8,178.8
XS GIS Cut Line= 3
2344219.53591897597939.5566576842343954.22081308597928.145460936
2343803.67726325597889.456843745
#Sta/Elev= 30
       0 3363.97    11.4 3364.18    27.4 3359.85    35.4 3356.64    43.9  3351.2
    51.4 3347.45    55.4 3346.56    63.4 3346.08    87.4 3346.42    99.5 3347.43
   103.5 3347.15   110.63344.673   115.5 3343.94   125.5 3344.79   131.5 3346.04
   135.5  3346.2   147.5 3346.28   167.5 3345.27   183.5 3346.12   191.5 3345.91
   195.5 3346.27   207.6 3349.91   211.6 3350.38   255.6  3351.8   288.3 3355.54
   325.5 3358.84   337.9 3360.52   355.1 3361.73   387.4 3365.55     421  3368.7
#Mann= 4 ,-1,0
       0     .06       0      80     .12       0   110.6    .045       0
   125.5     .12       0
Bank Sta=110.6,125.5
XS Rating Curve= 0 ,0
Exp/Cntr=0.3,0.1

Type RM Length L Ch R = 1 ,6170    ,110.9,113,104.4
XS GIS Cut Line= 4
2344331.06616297 597809.673335552344188.47686367597768.731853573
 2343911.0630289597806.8497850692343791.76802107597800.496796486
#Sta/Elev= 30
       0 3384.45    11.3 3382.12    44.6 3371.32    65.4 3366.36    77.9 3361.92
    94.6 3361.74   119.5 3357.09     149 3353.81   152.7  3353.1   160.8  3348.7
   164.8 3347.36   180.9 3344.38   253.6 3345.05   273.3 3343.54   306.1 3344.89
   318.2 3342.71   330.3 3341.92   334.4 3342.83   342.5 3348.22   346.5 3349.31
   366.7 3350.29   410.3 3357.04   447.3 3361.04   459.3 3363.09   476.2 3363.83
   503.4 3367.69   527.4 3368.74   531.6 3370.75   539.4 3372.28   547.8 3371.44
#Mann= 4 ,-1,0
       0     .06       0     100     .12       0   318.2    .045       0
   334.4     .12       0
Bank Sta=318.2,334.4
XS Rating Curve= 0 ,0
Exp/Cntr(USF)=0,0
Exp/Cntr=0.3,0.1

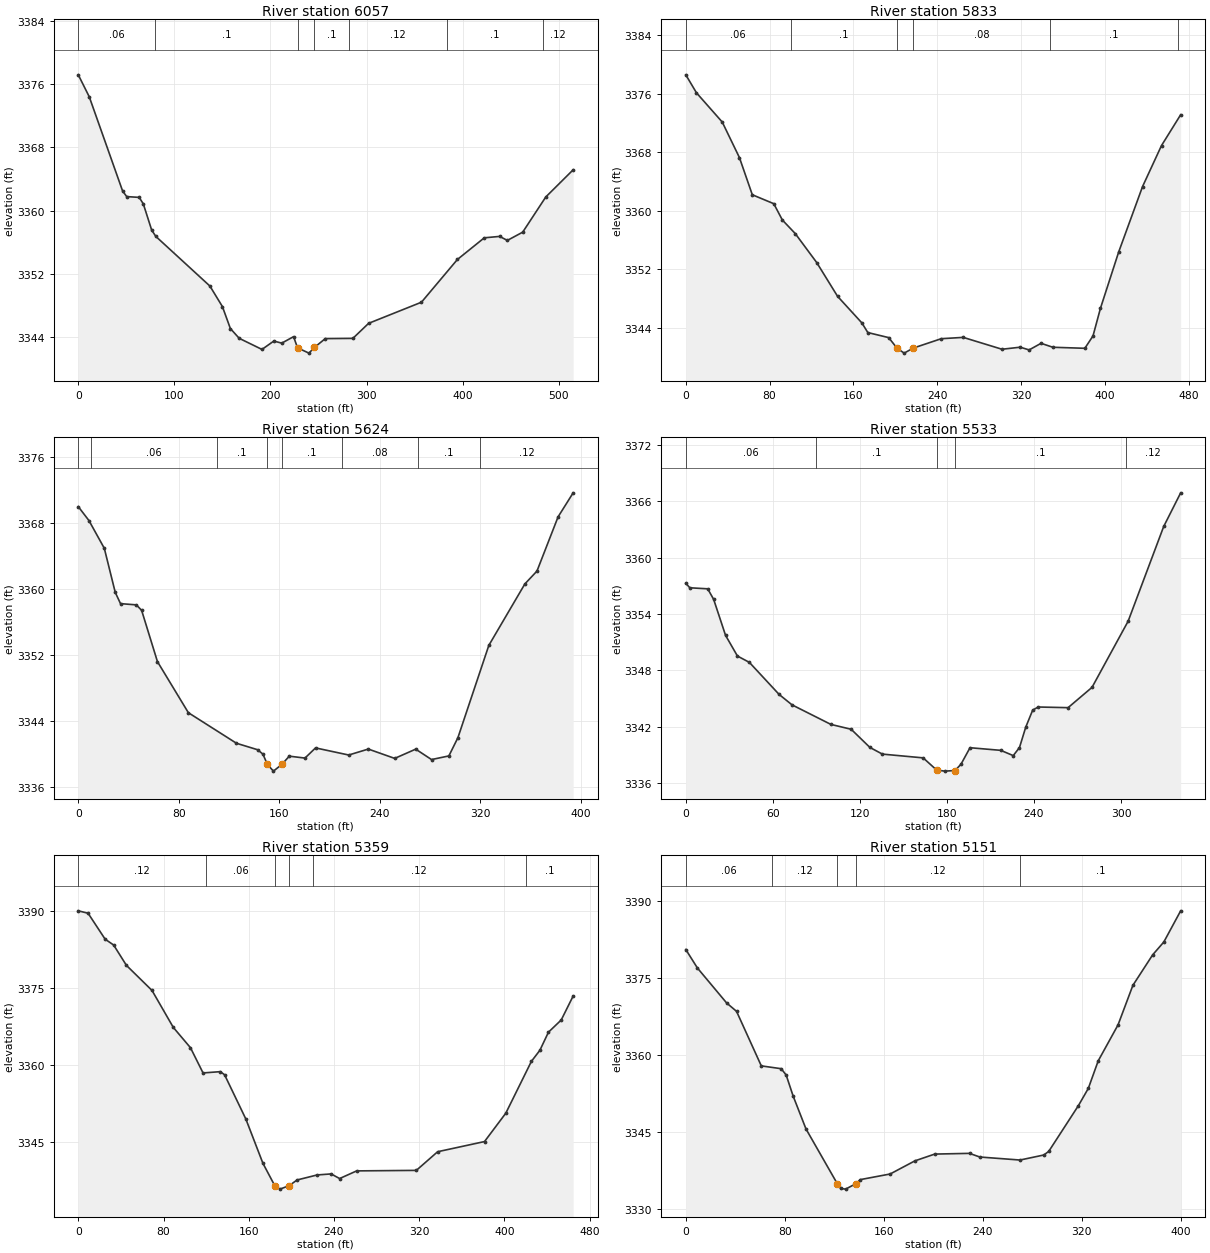
Type RM Length L Ch R = 1 ,6057    ,205,223.4,225.4
XS GIS Cut Line= 4
2344310.74048429597762.8510433812344170.13012797597704.692833179
2344013.32381439597742.2380068542343811.61052837597743.710366606
#Sta/Elev= 30
       0 3377.22    11.4 3374.44    46.1 3362.49    50.4 3361.77    63.4 3361.67
    67.7 3360.84    76.4 3357.52    80.7 3356.72     137 3350.42     150 3347.82
   158.3 3345.03   167.5 3343.79   191.2 3342.38   203.5 3343.44   211.8 3343.18
   224.1    3344   228.2 3342.58   240.1 3341.91   245.83342.636   257.1 3343.75
   285.8 3343.78   302.2 3345.69   357.2 3348.37   394.6 3353.79   422.6 3356.54
   438.6 3356.72   446.6 3356.21   462.6 3357.26   486.6 3361.72   515.1 3365.17
#Mann= 7 ,-1,0
       0     .06       0      80      .1       0   228.2    .045       0
   245.8      .1       0  282.16     .12       0   383.4      .1       0
   483.4     .12       0
Bank Sta=228.2,245.8
XS Rating Curve= 0 ,0
Exp/Cntr(USF)=0,0
Exp/Cntr=0.3,0.1

Type RM Length L Ch R = 1 ,5833    ,210.2,209.3,202.6
XS GIS Cut Line= 5
2344338.12503917597700.9666420252344198.35929036597669.201699112
2344135.69431273597628.373995046 2343982.9054379597497.123640012
2343935.78599682597472.980848334
#Sta/Elev= 30
       0 3378.57    10.2 3376.11    34.8 3372.12    51.2 3367.27    63.5 3362.19
      84 3360.97    92.2 3358.74   104.5 3356.89     125 3352.93   144.9 3348.32
   168.1 3344.69   173.8 3343.37   193.7 3342.68   201.73341.235   208.5 3340.56
   217.2 3341.25   243.9 3342.53   264.9 3342.71   301.9 3341.09   319.3 3341.37
   327.8    3341   339.2  3341.9   350.5 3341.36     381 3341.22   388.8 3342.91
   395.9 3346.68   413.3 3354.37   436.1 3363.31   454.2 3368.91   472.5 3373.12
#Mann= 6 ,-1,0
       0     .06       0     100      .1       0   201.7    .045       0
   217.2     .08       0  348.12      .1       0  469.54     .12       0
Bank Sta=201.7,217.2
XS Rating Curve= 0 ,0
Exp/Cntr(USF)=0,0
Exp/Cntr=0.3,0.1

Type RM Length L Ch R = 1 ,5624    ,104.2,91.1,90.6
XS GIS Cut Line= 2
2344340.24270203597535.0830512562343964.71048804597416.493931047
#Sta/Elev= 30
       0 3369.98     8.5 3368.29    20.7 3364.94    29.4 3359.61    33.6 3358.24
    46.2 3358.09    50.4 3357.43      63 3351.22    87.6 3345.04   125.9 3341.34
   142.7 3340.56   146.9 3340.03   150.5 3338.78   155.3 3337.97     1623338.782
   167.9 3339.78   180.4 3339.55   188.8 3340.78   215.2 3339.92   230.8 3340.64
   251.8 3339.51   268.5 3340.63   281.1 3339.37   294.9 3339.81   302.1 3342.02
   326.7 3353.19   355.4 3360.63     365 3362.18   381.8 3368.74   393.8 3371.65
#Mann= 8 ,-1,0
       0     .12       0      10     .06       0     110      .1       0
   150.5    .045       0     162      .1       0     210     .08       0
     270      .1       0     320     .12       0
Bank Sta=150.5,162
XS Rating Curve= 0 ,0
Exp/Cntr(USF)=0,0
Exp/Cntr=0.3,0.1

Type RM Length L Ch R = 1 ,5533    ,157.6,174.5,167.5
XS GIS Cut Line= 4
2344326.93644156597461.753474104 2344227.5521583597439.668077824
 2344095.7759605597388.135486505 2344000.8087565597364.577730474
#Sta/Elev= 30
       0 3357.26     2.8 3356.78    15.1 3356.67    19.2 3355.55    27.4 3351.72
    35.6 3349.52    43.8 3348.85    64.3 3345.44    73.2 3344.33     100 3342.25
     114 3341.73   126.9  3339.8   135.5 3339.09   163.6 3338.69   172.83337.409
   178.4 3337.28   185.63337.343   189.7 3338.02   195.9 3339.77   217.1 3339.49
   225.7 3338.93     230 3339.79   234.3 3341.95   239.1 3343.77   242.9  3344.1
   263.5 3344.03     280 3346.19   304.9 3353.23   329.4  3363.3   341.1 3366.88
#Mann= 5 ,-1,0
       0     .06       0      90      .1       0   172.8    .045       0
   185.6      .1       0   303.3     .12       0
Bank Sta=172.8,185.6
XS Rating Curve= 0 ,0
Exp/Cntr(USF)=0,0
Exp/Cntr=0.3,0.1

Type RM Length L Ch R = 1 ,5359    ,205.1,207.2,205.8
XS GIS Cut Line= 2
  2344457.420047597314.1402261052343992.94599285597309.904900383
#Sta/Elev= 30
       0 3390.09     9.2 3389.62    25.2 3384.57    33.2 3383.43    45.2 3379.47
    69.2 3374.59    89.2 3367.39   105.3 3363.44   117.1 3358.53   133.3 3358.78
   137.3 3358.18   157.3 3349.55   173.3 3340.94   184.5 3336.55   189.3 3335.91
   198.1  3336.6   205.3 3337.69   224.2 3338.67   237.3 3338.87   245.3 3337.97
   261.3 3339.46   317.3 3339.56   337.3 3343.19   381.3 3345.17   401.3  3350.7
   425.3 3360.78   433.3 3362.95   441.3 3366.46   453.3 3368.84   464.5 3373.51
#Mann= 6 ,-1,0
       0     .12       0     120     .06       0   184.5    .045       0
   198.1     .06       0     220     .12       0     420      .1       0
Bank Sta=184.5,198.1
XS Rating Curve= 0 ,0
Exp/Cntr(USF)=0,0
Exp/Cntr=0.3,0.1

Type RM Length L Ch R = 1 ,5151    ,159.6,163.5,166.8
XS GIS Cut Line= 2
 2344405.1843631597129.9035572082344005.65197002597115.785804803
#Sta/Elev= 30
       0 3380.61     9.4    3377      33 3370.19      41 3368.56      61 3357.93
    77.1 3357.38    81.1 3356.14    86.7 3352.06    97.1 3345.64   122.43334.965
   125.1 3334.04   129.1 3333.91   137.1 3334.93   141.1 3335.77   165.1 3336.86
   185.1 3339.42   201.1 3340.74   229.2 3340.88   237.5 3340.17     270 3339.58
   289.2 3340.56   293.2 3341.26   317.2 3350.19   325.2 3353.55   333.2 3358.92
   349.2 3365.92   361.2 3373.63   377.2 3379.58   386.2 3382.08   399.8 3388.15
#Mann= 5 ,-1,0
       0     .06       0      70     .12       0   122.4    .045       0
   137.1     .12       0     270      .1       0
Bank Sta=122.4,137.1
XS Rating Curve= 0 ,0
Exp/Cntr(USF)=0,0
Exp/Cntr=0.3,0.1

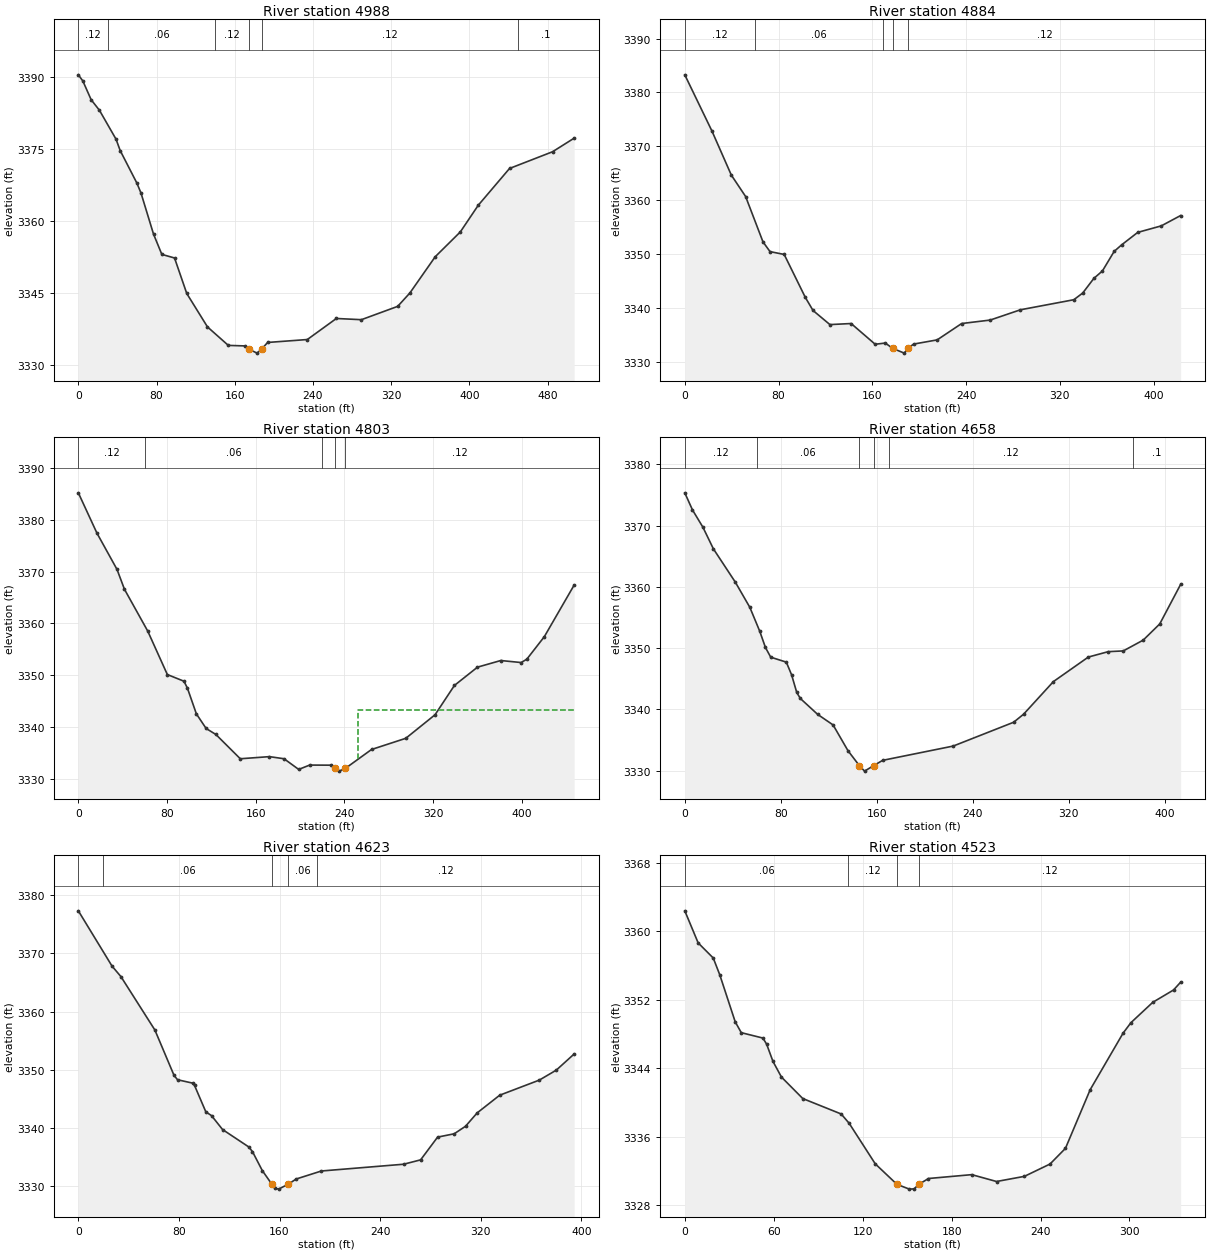
Type RM Length L Ch R = 1 ,4988    ,108.6,103.8,98
XS GIS Cut Line= 3
2344464.47892321597026.8439646462344135.53529215596908.254844437
2343978.12235282596905.431293955
#Sta/Elev= 30
       0 3390.47     4.6  3389.2    13.1 3385.29    21.6 3383.09    38.6 3377.06
    42.8 3374.71    59.9 3367.93    64.1 3365.86    76.9 3357.32    85.4  3353.1
    98.4 3352.35   110.9 3344.96   132.1    3338   153.4 3334.16   170.4 3334.05
   174.7 3333.35   182.8 3332.55   187.4 3333.38   193.6 3334.77   234.2 3335.38
   263.9 3339.76   289.5 3339.51   326.6 3342.28   339.1 3345.07     365 3352.61
   390.7 3357.78     409 3363.32     441 3370.98     485 3374.46   507.1 3377.29
#Mann= 6 ,-1,0
       0     .12       0      30     .06       0     140     .12       0
   174.7    .045       0   187.4     .12       0  449.67      .1       0
Bank Sta=174.7,187.4
XS Rating Curve= 0 ,0
Exp/Cntr(USF)=0,0
Exp/Cntr=0.3,0.1

Type RM Length L Ch R = 1 ,4884    ,75.7,81.4,86
XS GIS Cut Line= 5
 2344491.1045539596939.065762156 2344337.9791397596866.920134309
2344275.40385024596873.5457531932344211.35620103596825.694061254
2344123.01461591 596758.70169254
#Sta/Elev= 30
       0 3383.28    23.2 3372.82    39.7 3364.65    51.9 3360.67    66.7 3352.25
    72.7 3350.44    84.8 3349.91   102.8 3341.94   109.4  3339.5   123.8 3336.88
   141.9 3337.08   162.4 3333.23   171.1 3333.45   177.2 3332.48   187.2 3331.58
   190.7 3332.53   195.2 3333.26   215.3 3334.04   236.2 3337.08   260.5 3337.72
   286.3 3339.63   331.9  3341.5   339.5 3342.75     349 3345.47   356.3 3346.85
   366.3 3350.48   372.6 3351.68   386.4 3354.01   406.5 3355.22     423 3357.14
#Mann= 5 ,-1,0
       0     .12       0      60     .06       0  169.27     .12       0
   177.2    .045       0   190.7     .12       0
Bank Sta=177.2,190.7
XS Rating Curve= 0 ,0
Exp/Cntr(USF)=0,0
Exp/Cntr=0.3,0.1

Type RM Length L Ch R = 1 ,4803    ,143.6,144.7,138
XS GIS Cut Line= 3
 2344537.1853481596886.3723282072344225.87669437596745.092736173
2344142.35887248596680.802166787
#Sta/Elev= 30
       0 3385.24    16.8 3377.45    34.9 3370.44    41.6 3366.61    62.6 3358.53
    80.3 3350.13    95.3 3348.84    98.4 3347.51   106.5 3342.53   115.3 3339.71
   124.1 3338.55   146.1 3333.86   172.4 3334.27   185.6 3333.86   198.8  3331.8
   208.7 3332.64   228.3 3332.62   231.93332.018   235.2 3331.47   240.9    3332
   264.5 3335.65   295.4 3337.81   321.8 3342.36   339.3 3348.03   360.1 3351.56
   381.1 3352.84   399.5 3352.45   404.6  3353.1   420.4 3357.45   447.3 3367.42
#Mann= 5 ,-1,0
       0     .12       0      60     .06       0     220     .12       0
   231.9    .045       0   240.9     .12       0
#XS Ineff= 2 , 0
                          252.69         3343.26
Permanent Ineff=
       F       F
Bank Sta=231.9,240.9
XS Rating Curve= 0 ,0
Exp/Cntr(USF)=0,0
Exp/Cntr=0.3,0.1

Type RM Length L Ch R = 1 ,4658    ,34.2,34.8,38.4
XS GIS Cut Line= 3
 2344586.0717579596789.6212473312344371.10723412596698.334942709
2344198.10496326596649.747070894
#Sta/Elev= 30
       0 3375.34     6.4 3372.55    15.1 3369.73    23.8 3366.21    42.1 3360.77
    54.2 3356.66    62.5 3352.74    67.2 3350.11    71.6 3348.53    84.6 3347.72
      89 3345.65    93.3 3342.77    96.3 3341.79   110.7  3339.2   123.6 3337.47
     136 3333.27   145.5 3330.83   149.8 3329.94   157.4 3330.84   164.9  3331.7
   223.7 3334.03     274 3337.91   282.3 3339.22   307.2 3344.55   336.3 3348.55
   352.9 3349.43   365.4 3349.55     382 3351.31   395.8 3353.95   413.2  3360.4
#Mann= 6 ,-1,0
       0     .12       0      60     .06       0   145.5    .045       0
   157.4     .06       0     170     .12       0  373.54      .1       0
Bank Sta=145.5,157.4
XS Rating Curve= 0 ,0
Exp/Cntr(USF)=0,0
Exp/Cntr=0.3,0.1

Type RM Length L Ch R = 1 ,4623    ,98.1,100.3,101.6
XS GIS Cut Line= 2
2344606.36233488 596773.43030896 2344255.5361876596593.428965786
#Sta/Elev= 30
       0 3377.27    26.8 3367.79    33.9 3365.98    60.9 3356.82    76.1 3349.05
    78.9  3348.3    90.9 3347.72    92.4 3347.33   101.4 3342.79   105.9 3342.15
   114.7 3339.76   135.5 3336.78   138.5 3335.97   146.3 3332.72   153.93330.384
   156.3  3329.7   159.3 3329.54     167  3330.4   173.3 3331.28   193.3 3332.65
   258.7 3333.81   272.2 3334.56   285.7 3338.46   298.9 3339.03   307.9 3340.32
   317.2 3342.62   335.1 3345.65   366.6 3348.24   380.1 3349.95   394.3 3352.72
#Mann= 5 ,-1,0
       0     .12       0      20     .06       0   153.9    .045       0
     167     .06       0     190     .12       0
Bank Sta=153.9,167
XS Rating Curve= 0 ,0
Exp/Cntr(USF)=0,0
Exp/Cntr=0.3,0.1

Type RM Length L Ch R = 1 ,4523    ,100.1,101.6,102.8
XS GIS Cut Line= 3
2344623.61693158596692.445503701 2344524.9688282596624.716955111
2344348.28565796596502.511095697
#Sta/Elev= 30
       0 3362.38       9 3358.64    19.2 3356.87    23.6 3354.91      34 3349.43
    38.1 3348.16    52.7 3347.53    55.2 3346.82    59.5  3344.8    65.2 3342.98
    79.6 3340.47   105.5 3338.67   110.9 3337.58   128.5 3332.85   143.13330.459
   151.5  3329.9   154.7 3329.93  157.84 3330.45   164.4 3331.14   193.6 3331.59
   210.3 3330.79   229.1 3331.39   246.4 3332.83   256.8 3334.66   273.5 3341.51
   295.7 3348.11     301 3349.33   315.7  3351.7   329.7 3353.14   334.5 3354.05
#Mann= 4 ,-1,0
       0     .06       0     110     .12       0   143.1    .045       0
  157.84     .12       0
Bank Sta=143.1,157.84
XS Rating Curve= 0 ,0
Exp/Cntr(USF)=0,0
Exp/Cntr=0.3,0.1

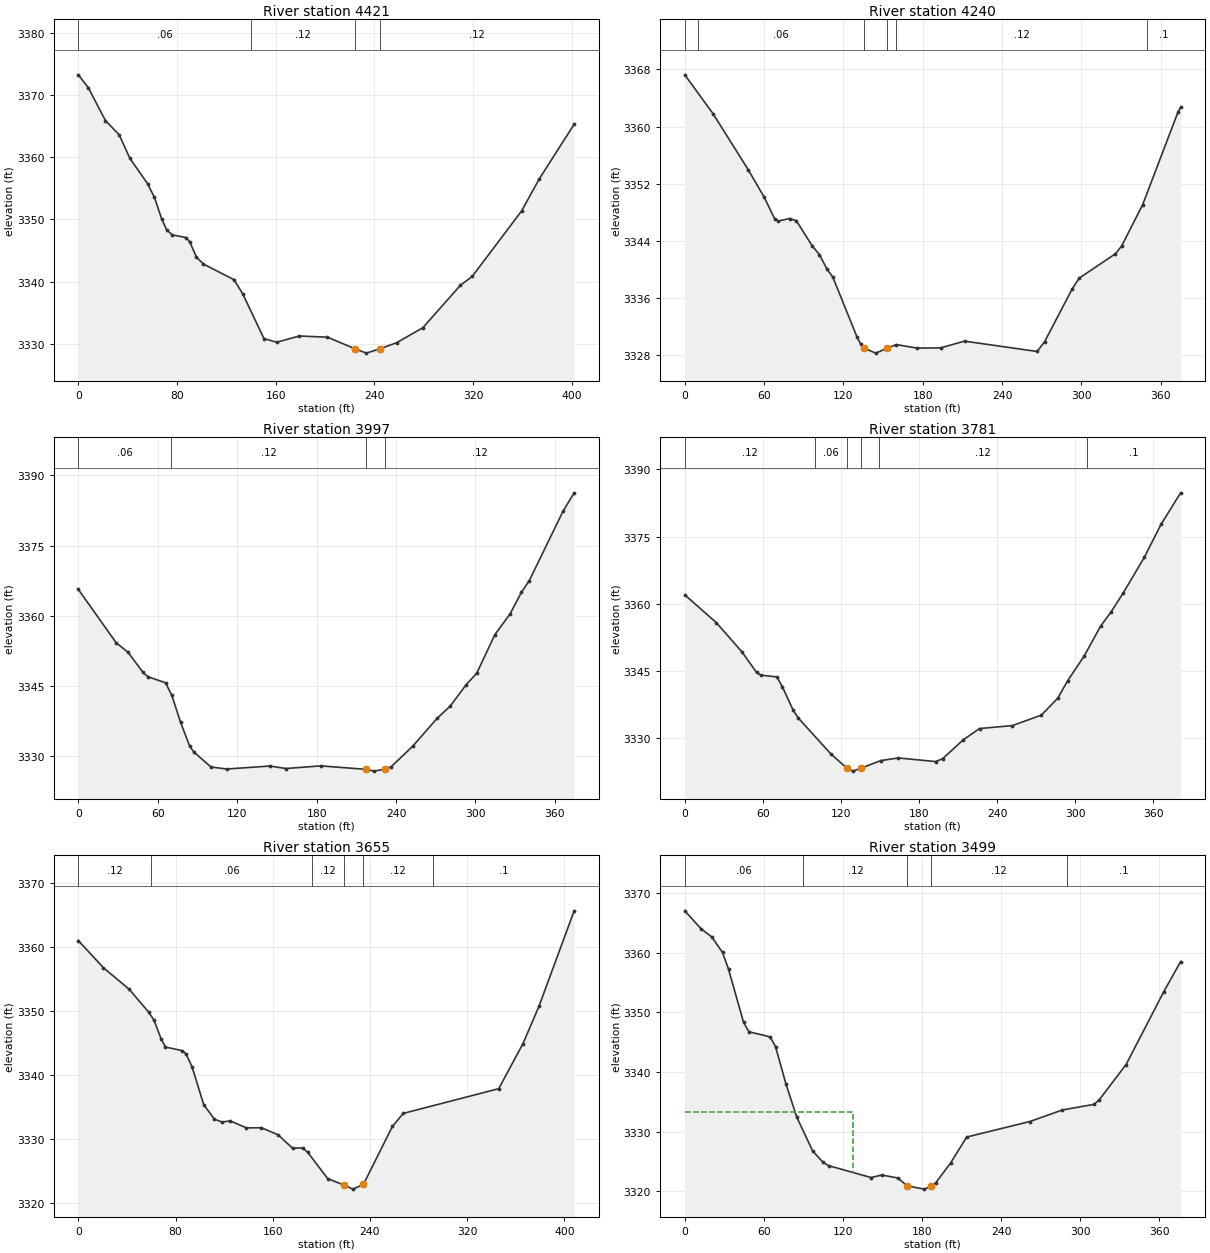
Type RM Length L Ch R = 1 ,4421    ,174.1,181.3,178.5
XS GIS Cut Line= 2
2344717.89257889596649.8999754092344393.89016118596412.015847371
#Sta/Elev= 30
       0 3373.22       8 3371.18      22 3365.87    33.2 3363.57    41.8  3359.8
    56.1 3355.75    61.7 3353.54    67.6 3350.07    71.6 3348.33    76.1 3347.51
    87.6 3347.07    90.4 3346.36    95.8 3343.93   101.4 3342.83   126.2 3340.32
   133.4    3338   150.5 3330.85   160.9 3330.27   179.2 3331.27     202 3331.08
   224.3 3329.22   233.5 3328.52   244.5 3329.22   258.1 3330.19   279.3  3332.6
   309.8 3339.42   319.4 3340.85   359.4 3351.36   373.7  3356.5     402 3365.28
#Mann= 4 ,-1,0
       0     .06       0     140     .12       0   224.3    .045       0
   244.5     .12       0
Bank Sta=224.3,244.5
XS Rating Curve= 0 ,0
Exp/Cntr(USF)=0,0
Exp/Cntr=0.3,0.1

Type RM Length L Ch R = 1 ,4240    ,241.1,242.7,236.4
XS GIS Cut Line= 2
2344796.24610474596572.9582247982344514.59694425596325.191670075
#Sta/Elev= 30
       0 3367.24    21.4 3361.79      48 3353.95    60.2 3350.07    67.9  3347.1
    70.7 3346.77    79.3 3347.12    84.4 3346.81    96.3 3343.32   101.9 3342.06
   107.6 3340.02     112 3338.92   130.3 3330.53   133.1 3329.53   135.9 3328.97
   144.4 3328.28   152.9 3328.94   159.9 3329.48   175.6 3328.99   193.5 3329.01
   211.6 3329.96   266.5 3328.51   272.2 3329.88   293.1 3337.28   298.4 3338.78
   325.8 3342.19   330.4 3343.25   346.4 3349.07     373 3361.97   375.1 3362.71
#Mann= 6 ,-1,0
       0     .12       0      10     .06       0   135.9    .045       0
   152.9     .06       0     160     .12       0     350      .1       0
Bank Sta=135.9,152.9
XS Rating Curve= 0 ,0
Exp/Cntr(USF)=0,0
Exp/Cntr=0.3,0.1

Type RM Length L Ch R = 1 ,3997    ,216.9,216.4,213
XS GIS Cut Line= 2
2344906.36457351596407.0746340292344604.95055964596184.720033637
#Sta/Elev= 30
       0 3365.64    28.7  3354.2    37.5 3352.23    48.7 3347.97    52.4    3347
    65.9 3345.68    70.6 3343.01    77.3  3337.2      84 3332.22    87.2  3330.9
   100.2 3327.69   112.1 3327.25   144.7 3327.89   156.8 3327.36   183.1 3327.92
   217.5 3327.18   223.2  3326.8   231.4 3327.21   236.3 3327.73   252.5 3332.09
   271.1  3338.1   281.1 3340.73   292.9 3345.24     301 3347.73   314.7 3355.97
   326.2 3360.41   334.7    3365   340.7 3367.53   366.2 3382.36   374.6 3386.29
#Mann= 4 ,-1,0
       0     .06       0      70     .12       0   217.5    .045       0
   231.4     .12       0
Bank Sta=217.5,231.4
XS Rating Curve= 0 ,0
Exp/Cntr(USF)=0,0
Exp/Cntr=0.3,0.1

Type RM Length L Ch R = 1 ,3781    ,123.7,126,123.6
XS GIS Cut Line= 5
2345002.74956771596247.7928586072344966.67675379596199.941166668
2344907.04618383596183.7452093962344890.85022656596177.119590512
2344661.89828513596099.820703534
#Sta/Elev= 30
       0    3362    24.2 3355.81    43.7 3349.35    55.1 3344.72    58.4 3344.09
    70.8  3343.7      75 3341.46    83.2 3336.31      87 3334.59   112.3 3326.49
  124.33  3323.4   129.1 3322.68   135.53323.354   150.5 3325.02     164 3325.62
   192.7 3324.81   198.1 3325.46   213.8 3329.64   226.4 3332.18   251.7 3332.84
   273.8 3335.16   286.5 3338.93     294 3342.79   306.7 3348.31   319.4 3355.01
   327.5 3358.21     337 3362.51   353.1 3370.43   365.8  3377.7   380.9 3384.76
#Mann= 6 ,-1,0
       0     .12       0   99.93     .06       0  124.33    .045       0
   135.5     .06       0  149.21     .12       0  309.21      .1       0
Bank Sta=124.33,135.5
XS Rating Curve= 0 ,0
Exp/Cntr(USF)=0,0
Exp/Cntr=0.3,0.1

Type RM Length L Ch R = 1 ,3655    ,155.7,155.8,153.1
XS GIS Cut Line= 3
2345031.84352406596222.9038059052344944.22506427 596074.72060694
2344716.14221758596014.412748818
#Sta/Elev= 30
       0 3360.94    20.6 3356.72    41.9 3353.34    57.8 3349.79    62.2 3348.55
    68.2 3345.57    71.7 3344.32    85.7 3343.75    88.6 3343.27    93.7 3341.18
   103.2 3335.32     112 3333.05   118.2  3332.6   125.1 3332.78   138.3 3331.69
   150.7 3331.71   164.4 3330.61   176.3 3328.51   184.6 3328.57   188.8 3327.88
   205.3 3323.75   218.5 3322.77     226 3322.12   234.63322.846   258.5 3331.91
   267.4 3333.95     346 3337.81     366 3344.86   379.1 3350.67   408.1  3365.6
#Mann= 6 ,-1,0
       0     .12       0      60     .06       0  192.15     .12       0
   218.5    .045       0   234.6     .12       0  292.15      .1       0
Bank Sta=218.5,234.6
XS Rating Curve= 0 ,0
Exp/Cntr=0.3,0.1

Type RM Length L Ch R = 1 ,3499    ,168.3,171.7,168
XS GIS Cut Line= 2
2345112.48375863595940.482917015 2344739.0692075595896.011996937
#Sta/Elev= 30
       0 3367.05    12.4 3364.02    20.5 3362.66    28.6 3360.07    33.2 3357.23
    44.6 3348.31    48.7 3346.75    64.8 3345.89    68.8 3344.26    76.8 3337.94
    84.9 3332.44      97 3326.74     105 3324.81   109.1 3324.28   141.3 3322.28
   149.4 3322.71   161.4 3322.22   168.8 3320.88   181.6 3320.34   186.8  3320.8
   190.4 3321.42   201.7 3324.76   213.8 3329.08   261.8 3331.69   286.3 3333.62
   310.5 3334.57   314.5 3335.37   334.7 3341.24   363.2 3353.43   376.1 3358.53
#Mann= 5 ,-1,0
       0     .06       0      90     .12       0   168.8    .045       0
   186.8     .12       0     290      .1       0
#XS Ineff= 2 , 0
           127.8 3333.33
Permanent Ineff=
       F       F
Bank Sta=168.8,186.8
XS Rating Curve= 0 ,0
Exp/Cntr(USF)=0,0
Exp/Cntr=0.3,0.1