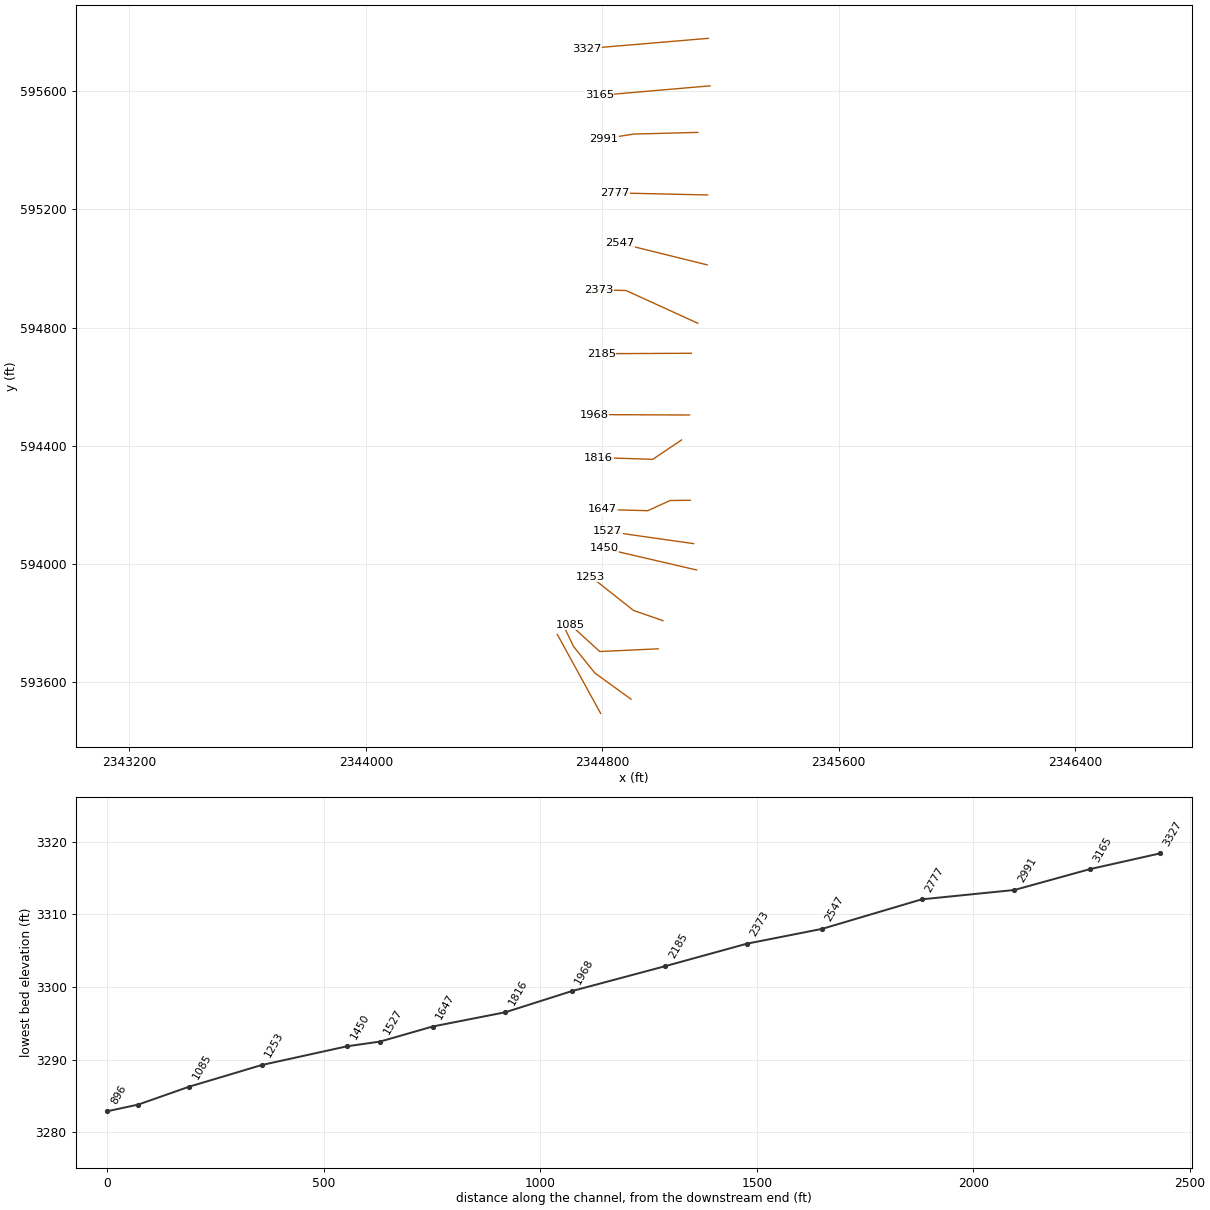
HEC-RAS study MLNXRN.prj: MLNXRN

--- MLNXRN.g01 (geometry) --- (continued)

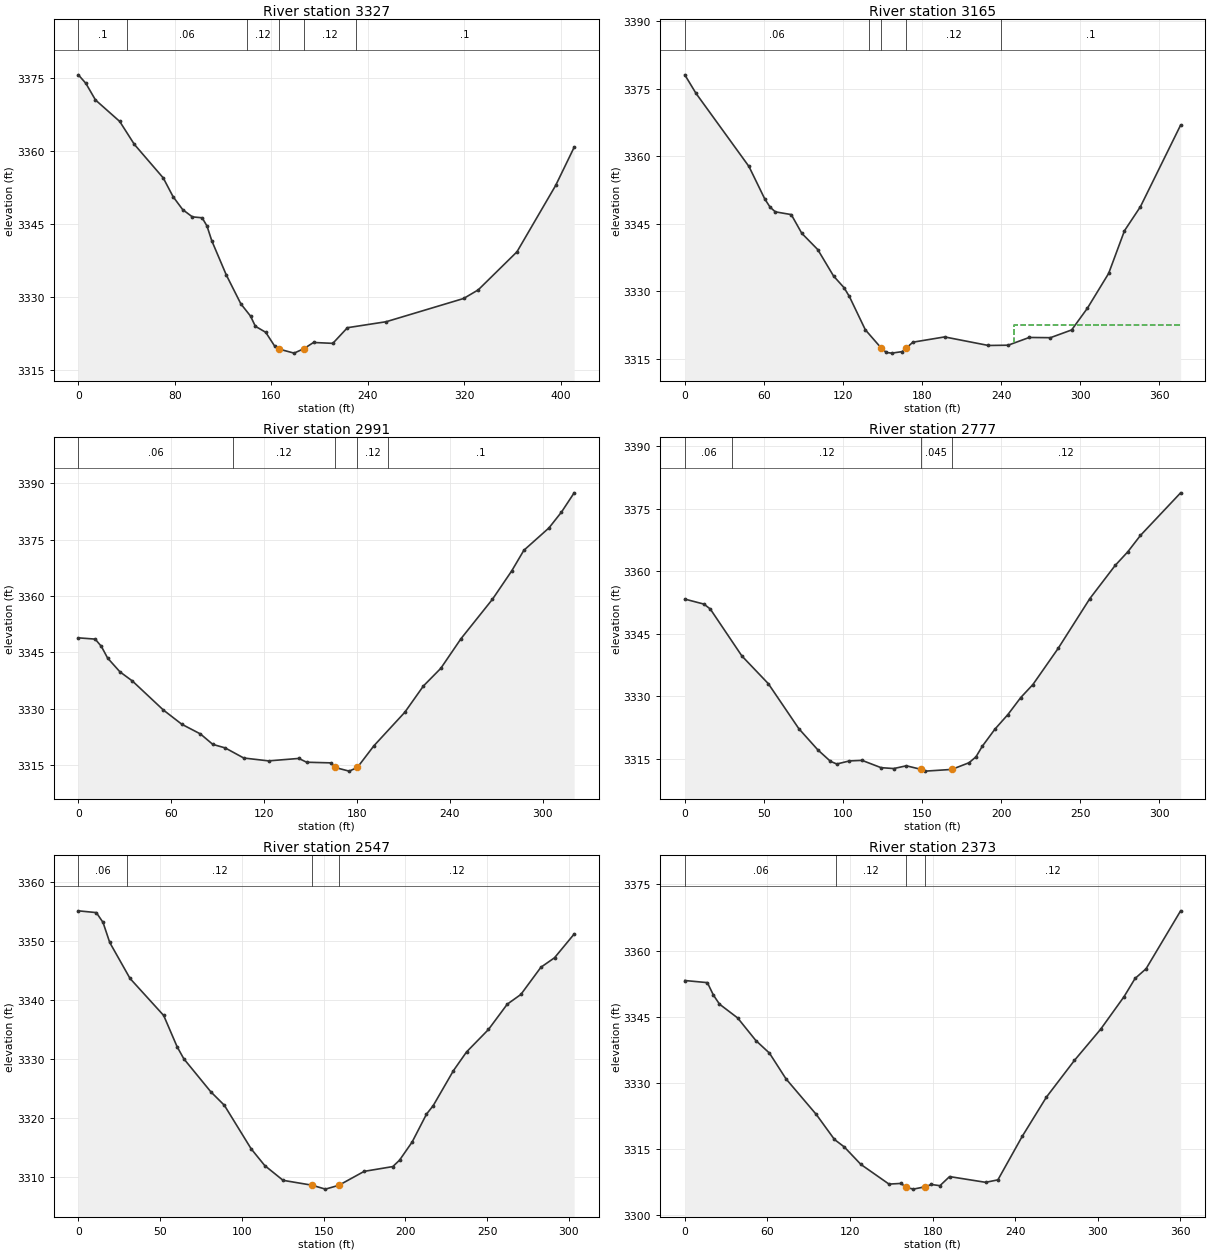
Type RM Length L Ch R = 1 ,3327    ,161.7,162.1,162
XS GIS Cut Line= 2
2345158.36645395595778.8346519682344748.95163418595744.246158574
#Sta/Elev= 30
       0 3375.66     6.2 3373.92    14.2 3370.49    34.3 3366.07    46.4 3361.36
    70.4 3354.44    78.5  3350.6    86.5 3347.93    94.5 3346.44   102.6 3346.25
   106.6 3344.57   110.6 3341.52   122.6  3334.5   134.7 3328.54   142.7 3326.03
   146.7 3323.94   155.3 3322.69   162.7 3319.86   166.4 3319.24   178.8 3318.41
   186.9 3319.32   194.9  3320.6   210.9 3320.42     223 3323.64   255.1 3324.87
   319.3 3329.65   331.4 3331.42   363.5 3339.25   395.6 3352.92   410.9 3360.76
#Mann= 6 ,-1,0
       0      .1       0      40     .06       0     140     .12       0
   166.4    .045       0   186.9     .12       0     230      .1       0
Bank Sta=166.4,186.9
XS Rating Curve= 0 ,0
Exp/Cntr(USF)=0,0
Exp/Cntr=0.3,0.1

Type RM Length L Ch R = 1 ,3165    ,173.6,174.1,169.9
XS GIS Cut Line= 2
2345164.65362616595618.0625865272344789.78518333 595585.68146273
#Sta/Elev= 30
       0 3378.05     8.5 3373.94    48.7 3357.69    60.7 3350.48    64.7 3348.67
    68.7 3347.62    80.8 3347.01    88.8 3342.85   100.9 3339.24   112.9 3333.37
   120.9 3330.76   124.9 3328.82     137 3321.43   149.1 3317.36     153 3316.38
   157.1 3316.24   165.1 3316.58   168.13317.366   173.1 3318.67   197.2 3319.84
   230.4 3317.94   245.4    3318   261.4 3319.72   277.5 3319.67   293.6 3321.39
   305.6 3326.24   321.7 3333.96   333.7 3343.43   345.8 3348.77   376.3 3366.89
#Mann= 5 ,-1,0
       0     .06       0     140     .12       0   149.1    .045       0
   168.1     .12       0     240      .1       0
#XS Ineff= 2 , 0
                          250.22         3322.59
Permanent Ineff=
       F       F
Bank Sta=149.1,168.1
XS Rating Curve= 0 ,0
Exp/Cntr=0.3,0.1

Type RM Length L Ch R = 1 ,2991    ,214,214.2,211.4
XS GIS Cut Line= 3
2345123.07207294595460.4793352172344905.65868589595454.832234254
2344804.01086857595438.596818988
#Sta/Elev= 30
       0 3348.86    10.9 3348.52    14.9 3346.57    18.9 3343.49    26.9  3339.8
    34.9 3337.38    54.9 3329.66    66.9 3325.84    78.9 3323.27    86.9 3320.49
    94.9 3319.55   106.9 3316.86   122.9  3316.1   142.5 3316.75   147.5 3315.74
     163 3315.57   165.9 3314.34     175 3313.37   180.3 3314.34     191 3320.12
     211 3329.06     223 3336.05   234.2 3340.73   247.3 3348.65   267.6 3359.13
     280 3366.65   287.9 3372.17   304.1 3378.12   312.2 3382.34   320.4 3387.47
#Mann= 5 ,-1,0
       0     .06       0     100     .12       0   165.9    .045       0
   180.3     .12       0     200      .1       0
Bank Sta=165.9,180.3
XS Rating Curve= 0 ,0
Exp/Cntr(USF)=0,0
Exp/Cntr=0.3,0.1

Type RM Length L Ch R = 1 ,2777    ,231.3,229.6,225.1
XS GIS Cut Line= 2
2345156.24879109595248.7130491292344842.83468768595255.771925332
#Sta/Elev= 30
       0 3353.36    12.1 3352.16    16.1 3350.99    36.1 3339.71    52.8 3333.07
    72.1 3322.27    84.1 3317.19    92.1 3314.43    96.1 3313.79   104.1 3314.53
   112.1 3314.66   124.1 3312.91   132.1  3312.7   140.1 3313.36   149.2 3312.52
   152.1 3312.08   168.8 3312.49   179.7 3314.09   184.1 3315.51   188.1 3318.05
   196.1 3322.16   204.3 3325.66   212.4 3329.73   220.1 3332.86   236.1 3341.55
   256.1 3353.48   272.1 3361.43   280.1 3364.71   288.1 3368.64   313.5 3378.86
#Mann= 4 ,-1,0
       0     .06       0      30     .12       0   149.2    .045       0
   168.8     .12       0
Bank Sta=149.2,168.8
XS Rating Curve= 0 ,0
Exp/Cntr(USF)=0,0
Exp/Cntr=0.3,0.1

Type RM Length L Ch R = 1 ,2547    ,175.9,174.1,171.4
XS GIS Cut Line= 2
2345154.83701585595012.2406963312344860.48187819595084.947121221
#Sta/Elev= 30
       0 3355.16      11 3354.86    15.1  3353.2    19.2  3349.8    31.6 3343.71
    52.2 3337.43    60.4 3332.14    64.5  3330.1      81 3324.51    89.3 3322.22
   105.7 3314.84     114 3312.01   125.2 3309.51   142.8 3308.69   151.1 3308.02
   159.3 3308.67   174.8 3311.03   192.3 3311.84   196.4 3312.92   204.1 3315.99
   212.9 3320.72     217 3322.16   229.4  3328.1   237.4 3331.26   250.8 3335.06
   262.3 3339.35   270.6 3340.99   282.9 3345.61   291.2 3347.21   303.2 3351.23
#Mann= 4 ,-1,0
       0     .06       0      30     .12       0   142.8    .045       0
   159.3     .12       0
Bank Sta=142.8,159.3
XS Rating Curve= 0 ,0
Exp/Cntr(USF)=0,0
Exp/Cntr=0.3,0.1

Type RM Length L Ch R = 1 ,2373    ,182.8,188.3,192.4
XS GIS Cut Line= 3
2345123.07207294594814.5921626492344880.24673156594925.416519035
2344787.06956568594927.534181896
#Sta/Elev= 30
       0 3353.21    16.4 3352.73    20.8  3349.9    25.2 3347.86    38.4 3344.73
    51.6 3339.62    61.5 3336.76    73.5 3330.94    95.5 3322.88   108.7 3317.21
   115.8 3315.53   127.9 3311.56   148.3 3307.11   157.1 3307.26   160.4 3306.43
   165.9 3305.97   174.7 3306.51   179.1 3307.02   185.3 3306.75   192.3 3308.81
   218.5 3307.51   227.4 3308.07     245 3317.89   262.6 3326.79     283 3335.13
     302 3342.17     319 3349.55     327 3353.67     335 3355.87   360.1 3368.99
#Mann= 4 ,-1,0
       0     .06       0     110     .12       0   160.4    .045       0
   174.7     .12       0
Bank Sta=160.4,174.7
XS Rating Curve= 0 ,0
Exp/Cntr(USF)=0,0
Exp/Cntr=0.3,0.1

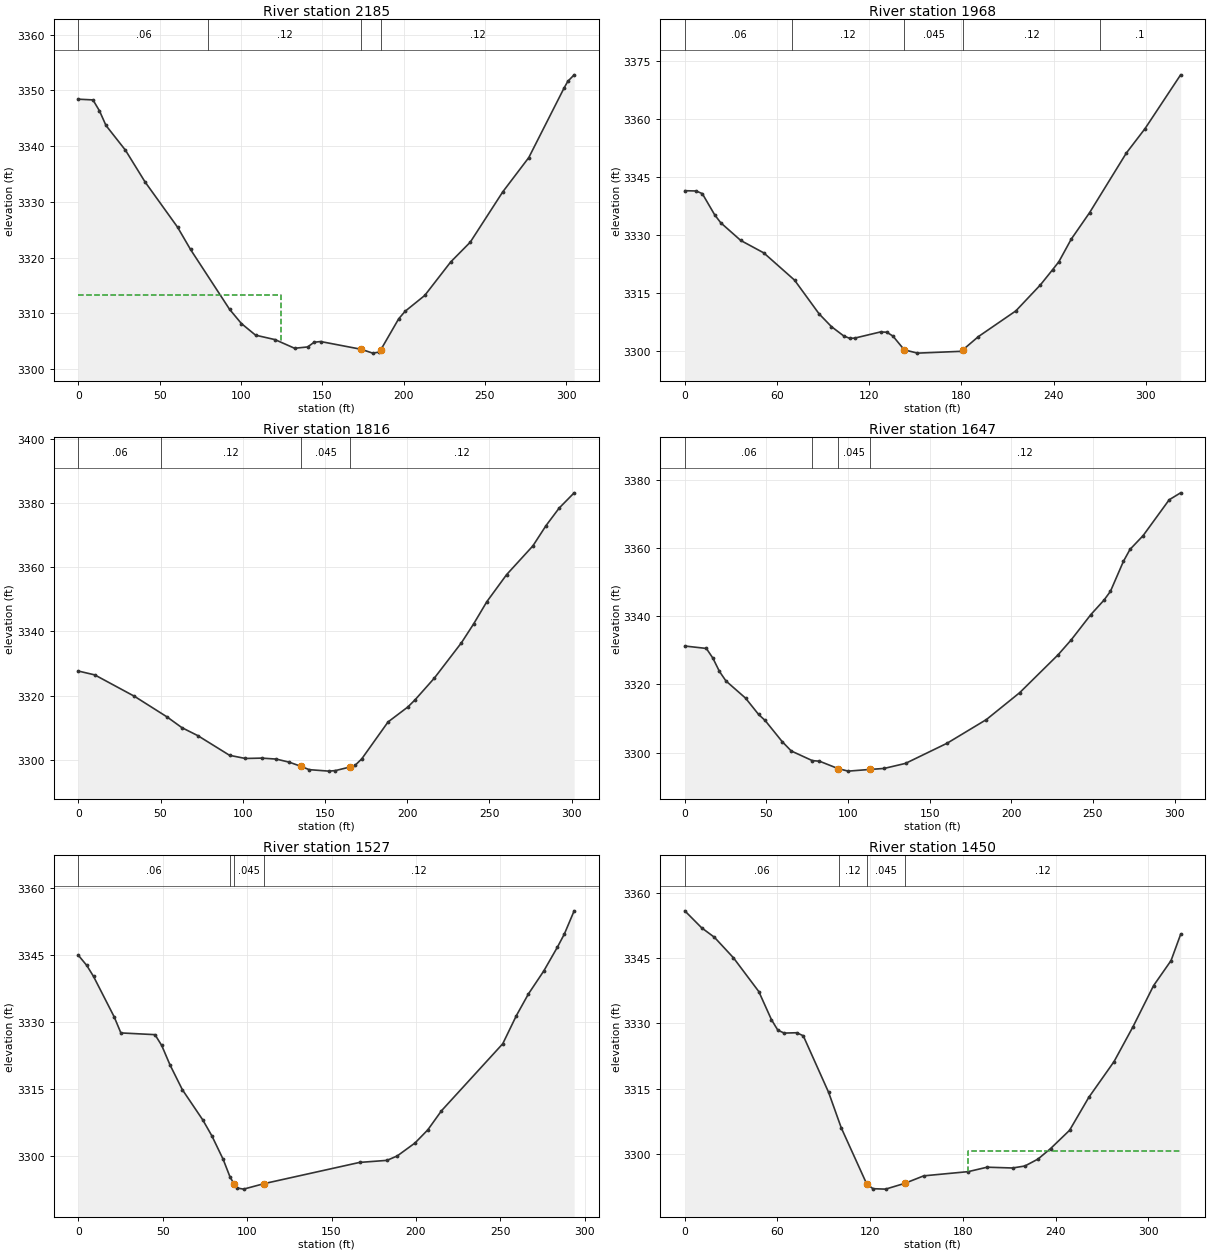
Type RM Length L Ch R = 1 ,2185    ,216.5,216.6,214.8
XS GIS Cut Line= 2
2345101.18955671594712.9443453272344796.24610474594711.532570086
#Sta/Elev= 30
       0 3348.43       9  3348.3      13 3346.34      17 3343.72      29 3339.27
      41  3333.6      61 3325.48      69 3321.47      93 3310.74   100.3 3308.18
     109  3306.1     121  3305.3     133 3303.75     141 3303.99     145 3304.83
     149 3304.96   174.1 3303.56     181 3302.88     185 3303.07   186.1 3303.53
     197 3309.04     201  3310.4     213 3313.22     229 3319.24     241 3322.78
     261 3331.81     277 3337.96   298.6 3350.38     301 3351.64   304.9  3352.8
#Mann= 4 ,-1,0
       0     .06       0      80     .12       0   174.1    .045       0
   186.1     .12       0
#XS Ineff= 2 , 0
          124.73 3313.26
Permanent Ineff=
       F       F
Bank Sta=174.1,186.1
XS Rating Curve= 0 ,0
Exp/Cntr(USF)=0,0
Exp/Cntr=0.3,0.1

Type RM Length L Ch R = 1 ,1968    ,152.1,152.7,150.4
XS GIS Cut Line= 2
2345095.54245575 594504.001609722344772.95181327594505.413384961
#Sta/Elev= 30
       0 3341.45     7.4 3341.38    11.4 3340.69    19.4 3335.24    23.4 3333.15
    36.4 3328.58    51.4 3325.36    71.4 3318.32    87.4 3309.58    95.4 3306.29
   103.4 3303.88   107.4 3303.24   110.7 3303.33   127.4 3304.92   131.4 3304.84
   135.4 3303.85   142.8 3300.28   151.4 3299.43   179.4 3299.89     1813300.302
     191  3303.7   215.4 3310.36   231.4  3317.1   239.4 3321.06   243.4 3323.09
   251.4  3328.9   263.4 3335.79   287.3 3351.21   299.4 3357.49   322.6 3371.43
#Mann= 5 ,-1,0
       0     .06       0      70     .12       0   142.8    .045       0
     181     .12       0     270      .1       0
Bank Sta=142.8,181
XS Rating Curve= 0 ,0
Exp/Cntr(USF)=0,0
Exp/Cntr=0.3,0.1

Type RM Length L Ch R = 1 ,1816    ,159.3,168.3,177
XS GIS Cut Line= 3
2345068.47792976 594419.786828842344970.61603558594353.956280895
2344787.06956568594360.000535181
#Sta/Elev= 30
       0 3327.68      10 3326.48    34.1 3319.83      54 3313.39      63 3310.06
    72.7 3307.57      92 3301.45   101.6 3300.47   111.6 3300.58   120.4 3300.28
   128.4  3299.3   135.63297.984   140.4 3296.99   152.4 3296.53   156.4  3296.7
   165.13297.798   168.4 3298.36   172.4 3300.35   188.4 3311.84   200.4 3316.48
   204.8 3318.71   216.5 3325.45     233 3336.46   240.5 3342.39   248.5 3349.28
   260.5 3357.68   276.5 3366.64   284.5 3372.96   292.5 3378.42   301.6 3383.15
#Mann= 4 ,-1,0
       0     .06       0      50     .12       0   135.6    .045       0
   165.1     .12       0
Bank Sta=135.6,165.1
XS Rating Curve= 0 ,0
Exp/Cntr(USF)=0,0
Exp/Cntr=0.3,0.1

Type RM Length L Ch R = 1 ,1647    ,128.5,120.8,112.1
XS GIS Cut Line= 4
2345097.35469799594215.3480564962345029.37580991594214.628980936
2344953.70467734594180.1297309412344801.19238845594184.254799184
#Sta/Elev= 30
       0 3331.24    13.2 3330.53    17.2 3327.69    21.2 3323.81    25.2    3321
    37.2 3315.97    45.2 3311.18    49.2 3309.41    59.6 3303.24    65.2 3300.47
    78.1 3297.64    82.5 3297.47    94.13295.267   100.1 3294.56   113.3 3295.05
   122.1 3295.35   135.2 3296.83   160.7 3302.75   184.7 3309.67   205.1 3317.55
   228.7 3328.69   236.7 3333.05   248.7 3340.45   256.7 3344.66   260.7 3347.26
   268.7  3356.1   272.7 3359.57   280.7 3363.59   296.7 3374.12   303.7 3376.15
#Mann= 4 ,-1,0
       0     .06       0   77.98     .12       0    94.1    .045       0
   113.3     .12       0
Bank Sta=94.1,113.3
XS Rating Curve= 0 ,0
Exp/Cntr(USF)=0,0
Exp/Cntr=0.3,0.1

Type RM Length L Ch R = 1 ,1527    ,77.6,76.5,75
XS GIS Cut Line= 2
2345109.12755979594068.7004256952344818.33650877 594109.92649875
#Sta/Elev= 30
       0 3344.94       5 3342.65       9 3340.19    21.2 3331.15    25.2 3327.52
    45.4 3327.13    49.4  3324.7    54.3 3320.35    61.6  3314.8    73.7 3308.02
    79.1 3304.44    85.8 3299.16    89.8 3295.27   92.13 3293.71    93.9 3292.75
    97.9 3292.49     110 3293.72   166.6 3298.48   182.8 3298.94   188.9 3299.93
   199.4 3302.83     207 3305.78   215.1 3310.06   251.4 3325.09   259.5 3331.42
   266.6 3336.26   275.7 3341.41   283.8 3346.77   287.9  3349.7   293.7  3354.9
#Mann= 4 ,-1,0
       0     .06       0      90     .12       0   92.13    .045       0
     110     .12       0
Bank Sta=92.13,110
XS Rating Curve= 0 ,0
Exp/Cntr(USF)=0,0
Exp/Cntr=0.3,0.1

Type RM Length L Ch R = 1 ,1450    ,204,197.6,188.3
XS GIS Cut Line= 2
2345118.83674722593979.5271078432344806.12853143594052.233532733
#Sta/Elev= 30
       0 3355.94    10.9 3352.03    19.2 3349.84    31.5 3345.12    47.9 3337.35
    56.1 3330.87    60.2 3328.47    64.3 3327.78    72.5 3327.86    76.7 3327.16
    93.1 3314.13   101.3 3305.95   117.7 3293.09   121.8 3291.94     130 3291.84
   142.4 3293.17   154.7  3294.9   183.5 3295.87   195.7 3296.89   212.2 3296.71
   220.2 3297.17   228.6 3298.75   236.8 3301.18   249.1 3305.39   261.5 3312.95
   277.9 3321.22   290.2 3329.27   303.5 3338.72   314.8 3344.48     321 3350.52
#Mann= 4 ,-1,0
       0     .06       0     100     .12       0   117.7    .045       0
   142.4     .12       0
#XS Ineff= 2 , 0
                          183.33         3300.57
Permanent Ineff=
       F       F
Bank Sta=117.7,142.4
XS Rating Curve= 0 ,0
Exp/Cntr(USF)=0,0
Exp/Cntr=0.3,0.1

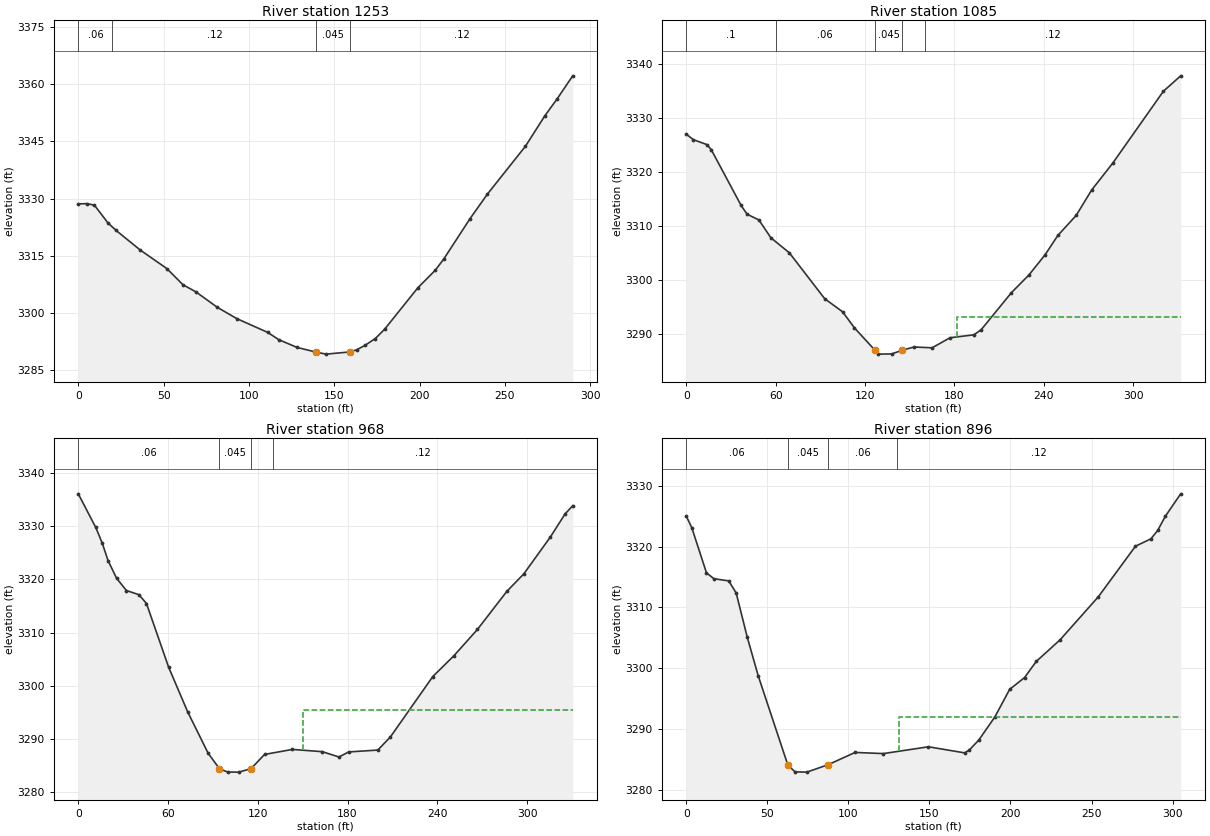
Type RM Length L Ch R = 1 ,1253    ,154.8,167.8,175.9
XS GIS Cut Line= 3
2345005.18884035593807.9964161122344905.65868589593842.584909506
2344760.95172373593956.938703994
#Sta/Elev= 30
       0 3328.64     5.3 3328.68     9.5 3328.27    17.4 3323.64    22.2 3321.66
    36.3 3316.54    51.9 3311.68    61.4 3307.42    68.8 3305.61    81.5 3301.52
    92.9 3298.56   111.1 3294.93   117.5 3293.04   128.2 3291.01   139.6 3289.75
   145.3 3289.25   159.5 3289.84   163.3 3290.41   168.1 3291.56   174.1 3293.34
   179.5 3295.75     199 3306.62   209.2 3311.21   214.3 3314.23   229.6 3324.75
   239.8 3331.19   262.1 3343.74   273.4 3351.67   280.6 3356.11   289.8 3362.19
#Mann= 4 ,-1,0
       0     .06       0      20     .12       0   139.6    .045       0
   159.5     .12       0
Bank Sta=139.6,159.5
XS Rating Curve= 0 ,0
Exp/Cntr(USF)=0,0
Exp/Cntr=0.3,0.1

Type RM Length L Ch R = 1 ,1085    ,126.4,116.8,106.7
XS GIS Cut Line= 3
2344988.95342508593712.701587373 2344791.3048914593703.525048309
2344692.48062456593793.878663706
#Sta/Elev= 30
       0 3326.97     4.8 3325.95    13.9 3325.03    16.8 3324.09    36.8 3313.79
    40.8 3312.16    48.8 3311.08    56.8 3307.79    69.2 3305.01    92.9 3296.52
   104.9  3294.1   112.9 3291.11   126.6    3287   128.9 3286.26     138  3286.3
   144.9 3286.99   152.9 3287.58     165 3287.43     177 3289.29     193 3289.83
   197.9 3290.77   218.2 3297.63     230 3300.92   240.9 3304.68   249.4 3308.23
   261.7 3311.94     272 3316.61   286.2  3321.6   320.2 3334.91   331.8 3337.76
#Mann= 5 ,-1,0
       0      .1       0      60     .06       0   126.6    .045       0
   144.9     .06       0     160     .12       0
#XS Ineff= 2 , 0
                          181.41         3293.19
Permanent Ineff=
       F       F
Bank Sta=126.6,144.9
XS Rating Curve= 0 ,0
Exp/Cntr(USF)=0,0
Exp/Cntr=0.3,0.1

Type RM Length L Ch R = 1 ,968     ,77.7,71.5,63.1
XS GIS Cut Line= 4
 2344897.1077555593542.3318143672344774.90189609593630.673399485
2344702.75626825593720.4873443552344674.78143296593778.645554558
#Sta/Elev= 30
       0 3336.05    11.7 3329.73      16 3326.82    19.9 3323.53    25.6  3320.2
    32.2  3317.9    40.6 3317.11    45.6 3315.46    60.4 3303.51    73.1 3295.14
    86.8 3287.36    94.4 3284.44    99.9 3283.82   107.3 3283.81   115.53284.467
   124.5 3287.13   143.1 3288.07   163.1 3287.65   174.3 3286.65   180.7  3287.6
   200.2 3287.95   208.6  3290.4     237 3301.76     251 3305.63   266.8 3310.59
   286.4 3317.72   297.8 3321.02   315.6 3327.96   325.4 3332.28   330.5 3333.82
#Mann= 4 ,-1,0
       0     .06       0    94.4    .045       0   115.5     .06       0
     130     .12       0
#XS Ineff= 2 , 0
                          150.06         3295.38
Permanent Ineff=
       F       F
Bank Sta=94.4,115.5
XS Rating Curve= 0 ,0
Exp/Cntr(USF)=0,0
Exp/Cntr=0.3,0.1

Type RM Length L Ch R = 1 ,896     ,188.9,183.8,174.1
XS GIS Cut Line= 2
2344794.27707044593494.2160354592344647.60930934593761.669011592
#Sta/Elev= 30
       0 3325.03     3.4 3323.12    12.5 3315.67    17.1 3314.71    26.2 3314.36
    30.8 3312.37    37.6 3305.13    44.4 3298.74    62.7 3284.04    62.7 3284.02
    67.2 3282.93    74.4 3282.89    87.6 3284.12   104.2 3286.13   121.6 3285.94
   149.4 3287.06   171.7 3286.06   174.6 3286.52   180.5 3288.18   190.4 3291.98
   199.5 3296.51   208.7 3298.45   215.9  3301.1   230.6 3304.66   254.2 3311.74
   277.1 3320.06   286.6 3321.27   290.8 3322.65   295.5 3324.98     305 3328.68
#Mann= 4 ,-1,0
       0     .06       0    62.7    .045       0    87.6     .06       0
     130     .12       0
#XS Ineff= 2 , 0
                          131.18         3291.95
Permanent Ineff=
       F       F
Bank Sta=62.7,87.6
XS Rating Curve= 0 ,0
Exp/Cntr(USF)=0,0
Exp/Cntr=0.3,0.1