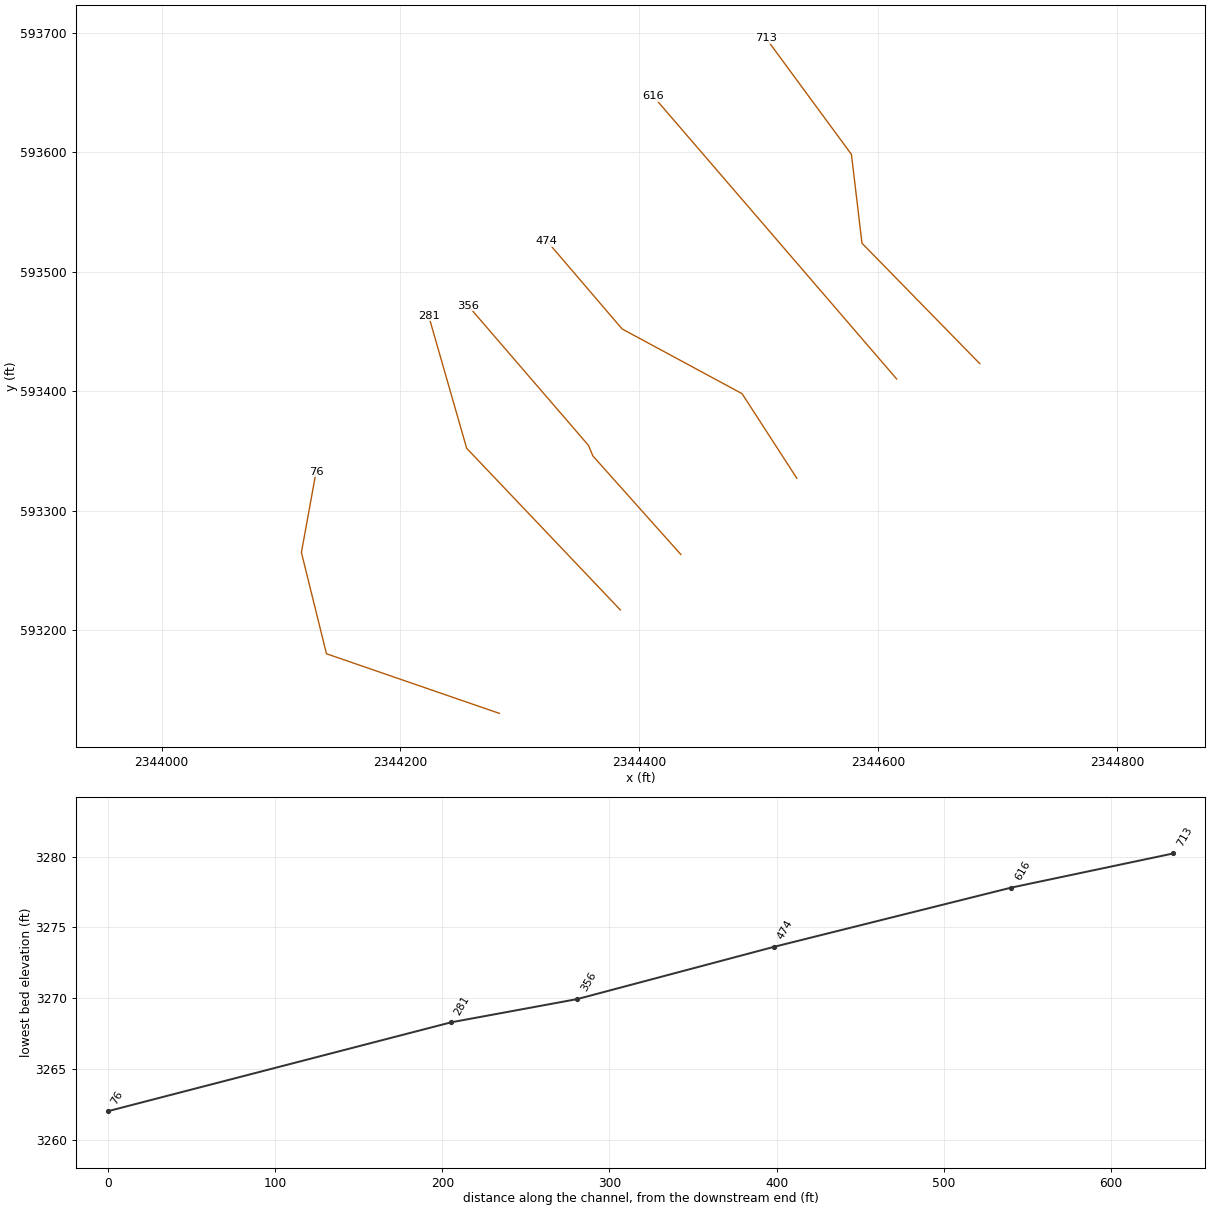
HEC-RAS study MLNXRN.prj: MLNXRN

--- MLNXRN.g01 (geometry) --- (continued)

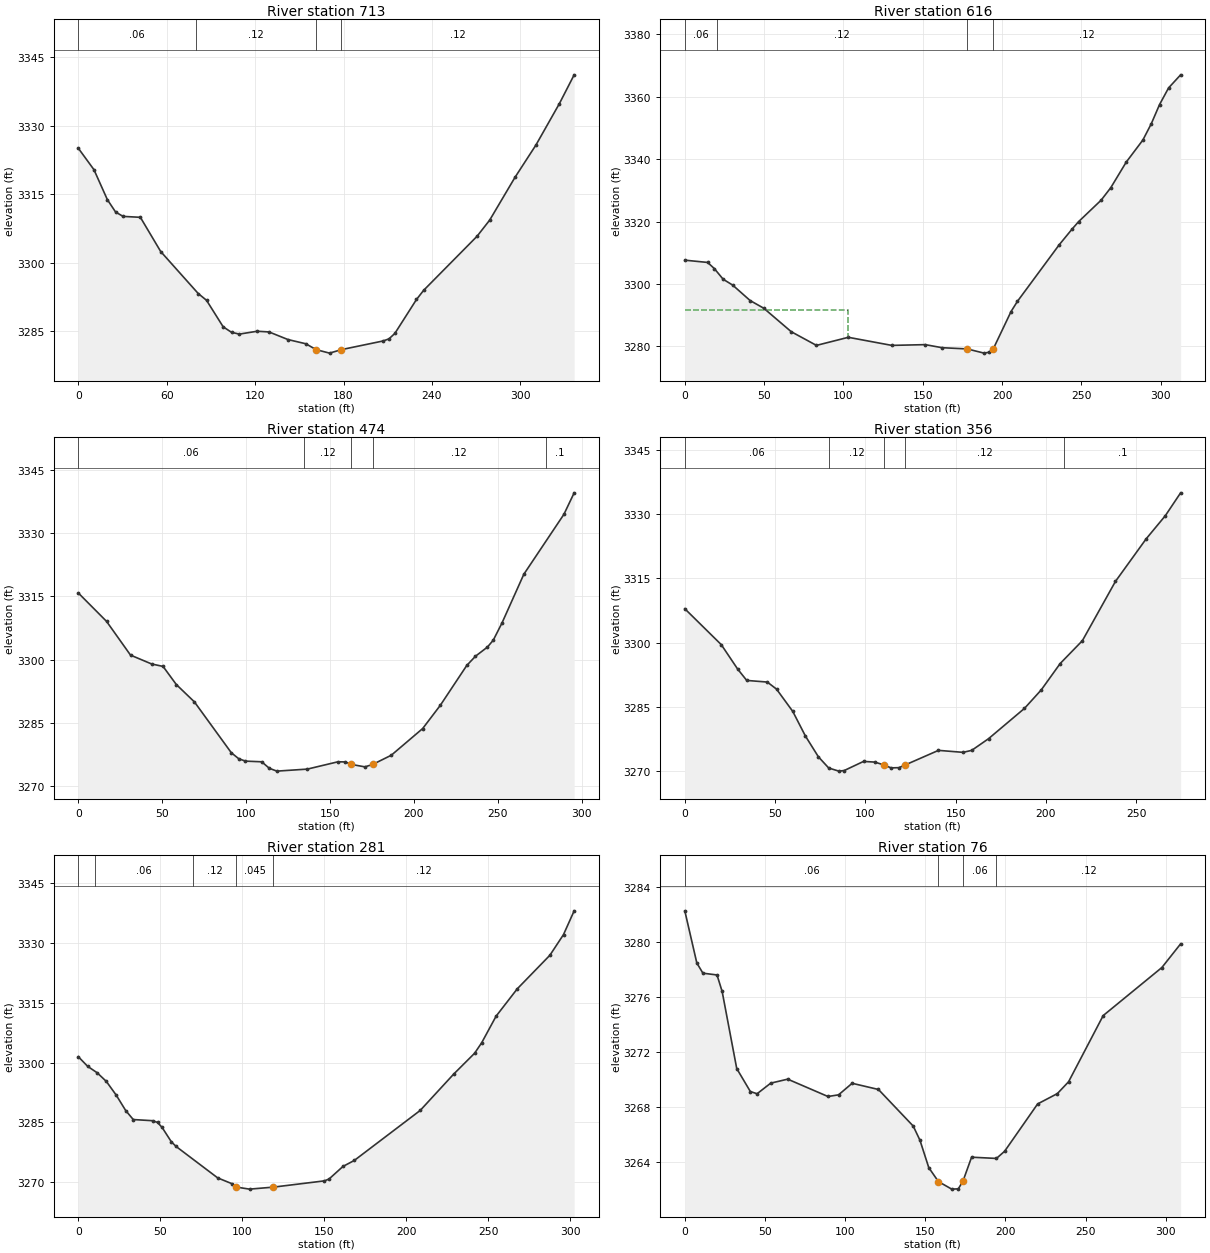
Type RM Length L Ch R = 1 ,713     ,86.5,96.9,102.5
XS GIS Cut Line= 4
2344685.08795122593423.0706744582344586.43984784593523.927317467
2344577.60568933593598.2814849422344506.19624136593695.457228572
#Sta/Elev= 30
       0 3325.08    10.6 3320.39    19.7 3313.83    25.3 3311.11    30.4 3310.16
    42.1 3309.96    55.9 3302.47    81.4 3293.26      87 3291.79    98.3 3285.98
     104 3284.77   109.3 3284.39   121.4 3285.01   129.4 3284.86   142.3 3283.19
   154.4 3282.27   161.43280.981   170.5 3280.22   178.6 3280.99   206.8 3282.88
   210.8 3283.34   214.8 3284.53   229.5 3291.97   234.4 3293.99   270.6 3305.81
   279.2 3309.36   296.3 3318.69   310.6 3325.81   326.5 3334.87   336.5 3341.16
#Mann= 4 ,-1,0
       0     .06       0      80     .12       0   161.4    .045       0
   178.6     .12       0
Bank Sta=161.4,178.6
XS Rating Curve= 0 ,0
Exp/Cntr(USF)=0,0
Exp/Cntr=0.3,0.1

Type RM Length L Ch R = 1 ,616     ,136.6,142,145.8
XS GIS Cut Line= 2
2344615.45220663593410.2938406022344411.52911633593647.158353189
#Sta/Elev= 30
       0 3307.61    14.4 3306.88    18.6 3304.92    24.2 3301.49    30.2 3299.61
    41.2 3294.66    49.8  3292.2    67.1 3284.68      83 3280.29   103.1 3282.88
   130.5 3280.29   151.6 3280.53   162.2 3279.55     178 3279.16   188.7 3277.81
   191.6 3278.08   194.4 3279.09   205.7 3291.15   209.7  3294.4     236 3312.51
   244.1 3317.53   248.3 3319.97   262.5 3326.85   268.6 3330.87   278.3 3339.04
   288.8 3346.12   294.1 3351.34   299.3 3357.47     305 3362.82   312.6 3367.02
#Mann= 4 ,-1,0
       0     .06       0      20     .12       0     178    .045       0
   194.4     .12       0
#XS Ineff= 2 , 0
          103.13 3291.66
Permanent Ineff=
       F       F
Bank Sta=178,194.4
XS Rating Curve= 0 ,0
Exp/Cntr(USF)=0,0
Exp/Cntr=0.3,0.1

Type RM Length L Ch R = 1 ,474     ,120.9,117.5,109.1
XS GIS Cut Line= 4
2344531.89713066593327.1042891472344486.04697676593397.963617901
2344385.59345776593452.1501634192344322.57264077593525.830242346
#Sta/Elev= 30
       0 3315.82    16.8 3309.11    31.1 3301.11    43.7 3299.01    50.5 3298.43
    58.4 3294.14    69.2 3290.02    91.2 3277.97    95.6 3276.57    99.6    3276
   109.3 3275.84   113.8 3274.31   118.3 3273.63   136.5 3274.11   154.7 3275.84
   159.2 3275.81   162.73275.217   170.8 3274.64   175.4 3275.21   186.5 3277.39
   205.2 3283.71   215.7  3289.2   231.5 3298.66   236.7 3300.85   243.8 3303.01
   247.3 3304.65   252.5 3308.73   265.5 3320.26   289.4 3334.46   295.5 3339.55
#Mann= 5 ,-1,0
       0     .06       0   134.4     .12       0   162.7    .045       0
   175.4     .12       0  278.54      .1       0
Bank Sta=162.7,175.4
XS Rating Curve= 0 ,0
Exp/Cntr(USF)=0,0
Exp/Cntr=0.3,0.1

Type RM Length L Ch R = 1 ,356     ,75,75.5,77.4
XS GIS Cut Line= 4
2344434.78679339593263.3196413692344361.16880579593345.771787479
2344357.48790641593354.605945991 2344256.6312634593471.658546273
#Sta/Elev= 30
       0 3307.89    20.2  3299.5    29.3 3293.78    34.3 3291.14    45.7 3290.76
    50.8 3289.11    59.8  3283.9    66.8 3278.15      74 3273.29    79.7 3270.68
    85.3 3269.95    88.3 3270.09      99 3272.22   105.2 3272.06   110.5 3271.37
   114.2 3270.71   118.6 3270.76   122.1  3271.4   140.5  3274.8   154.1 3274.34
   158.9  3274.8   168.2 3277.52   188.1  3284.6   197.4 3288.92   207.9 3295.09
   220.2 3300.43   238.5 3314.27   255.5 3324.21   266.1 3329.61   274.6 3334.97
#Mann= 5 ,-1,0
       0     .06       0      80     .12       0   110.5    .045       0
   122.1     .12       0  210.11      .1       0
Bank Sta=110.5,122.1
XS Rating Curve= 0 ,0
Exp/Cntr(USF)=0,0
Exp/Cntr=0.3,0.1

Type RM Length L Ch R = 1 ,281     ,196.2,205.3,196.2
XS GIS Cut Line= 3
2344384.11785296593216.9051818452344255.46983416593352.242897621
 2344223.5651255593463.394785862
#Sta/Elev= 30
       0 3301.46     5.7 3299.05    11.5 3297.44    17.1 3295.27    23.1 3291.85
    28.9 3287.98    33.5 3285.73    45.4 3285.44    48.3    3285    51.1 3283.75
    56.7 3280.18    59.6    3279      85 3271.12    93.5  3269.7    96.4 3268.82
   104.4 3268.31     119 3268.81   150.1 3270.38   152.9 3270.84   161.4 3273.99
   168.3 3275.49   208.5 3288.01   228.9  3297.1   241.7 3302.34     246 3304.96
   254.8 3311.62   267.7 3318.46   287.6 3326.87   295.9 3332.04   302.4 3337.99
#Mann= 5 ,-1,0
       0      .1       0      10     .06       0      70     .12       0
    96.4    .045       0     119     .12       0
Bank Sta=96.4,119
XS Rating Curve= 0 ,0
Exp/Cntr(USF)=0,0
Exp/Cntr=0.3,0.1

Type RM Length L Ch R = 1 ,76      ,,,
XS GIS Cut Line= 4
2344282.84488368593130.2847748762344138.08840295593180.203338161
2344117.10053289593265.0177209172344129.42737818593332.673485884
#Sta/Elev= 30
       0 3282.26     7.5 3278.47    11.3 3277.73    20.1  3277.6    23.3  3276.4
    32.4  3270.8    40.9 3269.13    45.1 3268.97    53.6 3269.74    64.2 3270.03
    89.3 3268.77    95.9 3268.89   104.4 3269.73   120.8 3269.28   142.5 3266.62
   146.7 3265.59   152.2  3263.6   158.2 3262.59   166.5 3262.04   170.6 3262.06
  173.49 3262.61   178.9 3264.36   194.4 3264.27   199.5 3264.79   220.1 3268.23
   232.4 3268.98   239.4 3269.84     261 3274.65   297.6 3278.14   309.3 3279.86
#Mann= 4 ,-1,0
       0     .06       0   158.2    .045       0  173.49     .06       0
   194.4     .12       0
Bank Sta=158.2,173.49
XS Rating Curve= 0 ,0
Exp/Cntr(USF)=0,0
Exp/Cntr=0.3,0.1
LCMann Table=0

Chan Stop Cuts=-1
Use User Specified Reach Order=0
Composite Channel Slope=5